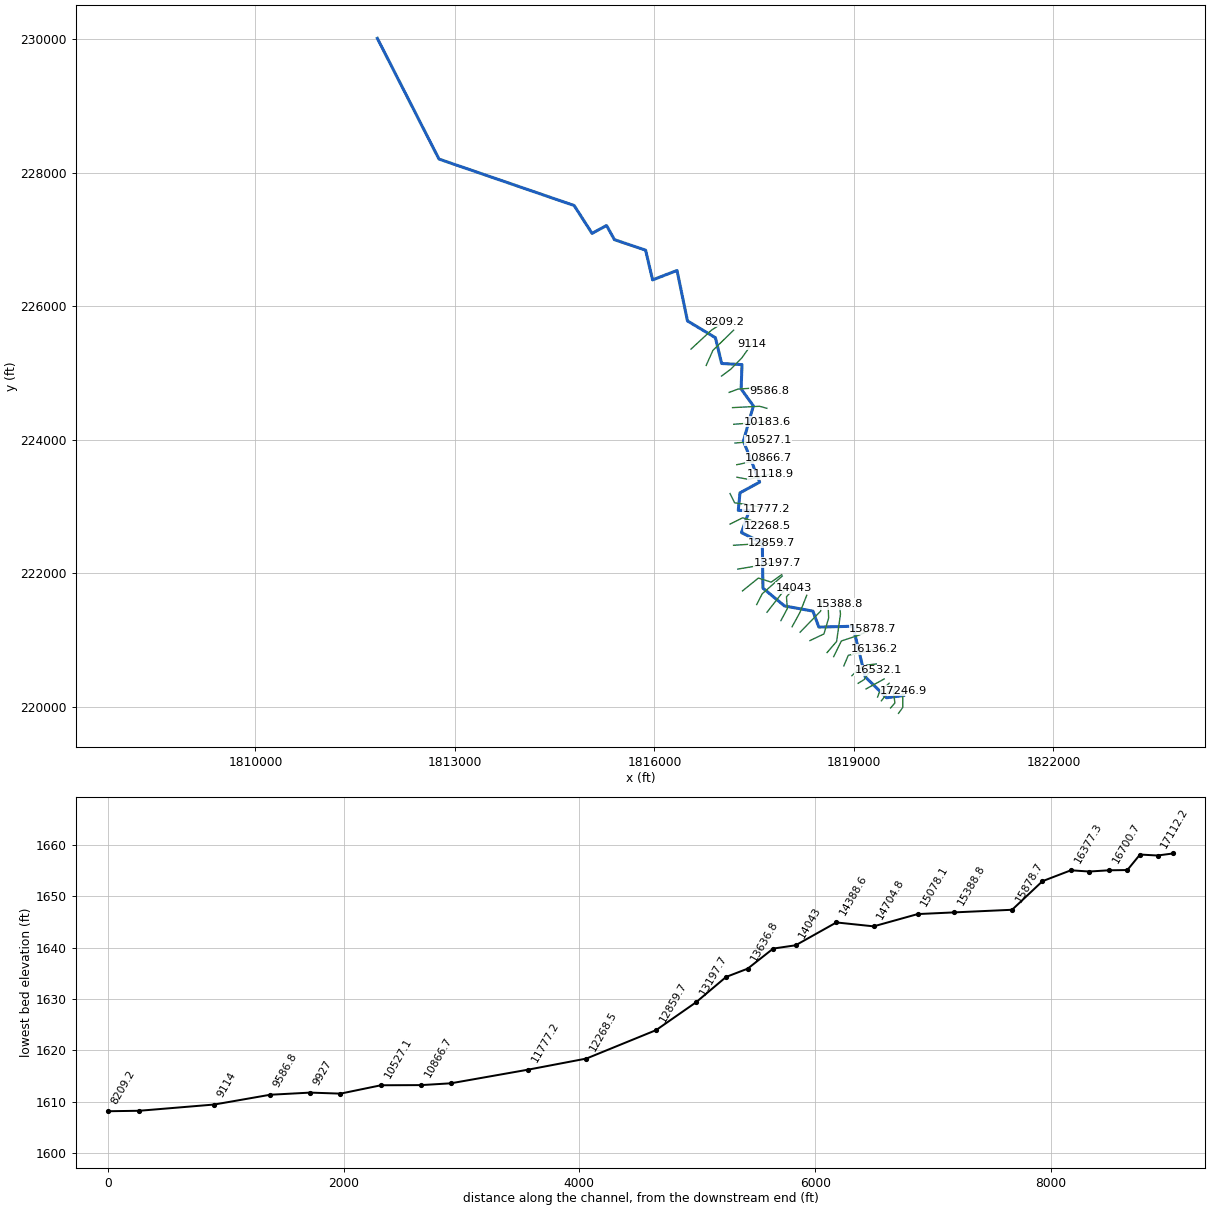
--- LLAURELRN.prj (project) ---

Proj Title=LLAURELRN
Current Plan=p01
Default Exp/Contr=0,0
English Units
Geom File=g01
Flow File=f01
Plan File=p01
BEGIN DESCRIPTION:
END DESCRIPTION:
DSS Export Rating Curves= 0
DSS Export Rating Curve Sorted= 0
DSS Export Volume Flow Curves= 0
DXF OffsetX= 0
DXF OffsetY= 0
DXF ScaleX= 0
DXF ScaleY= 0

--- LLAURELRN.p01 (plan) ---

Plan Title=Floodplain
Program Version=4.00
Geom File=g01
Flow File=f01
K Sum by GR=0
Std Step Tol=0.01
Critical Tol=0.01
Num of Std Step Trials=20
Max Error Tol=0.3
Flow Tol Ratio=0.001
Split Flow NTrial=30
Split Flow Tol=0.02
Split Flow Ratio=0.02
Log Output Level=0
Friction Slope Method=1
Unsteady Friction Slope Method=2
Unsteady Bridges Friction Slope Method=1
Global Log Level=0
CheckData=False
Run HTab=0
Run UNet=0
Run PostProcess=0
UNET Theta=0
UNET Theta Warmup=0
UNET ZTol=0
UNET ZSATol=0
UNET MxIter=0
UNET MaxInSteps=0
UNET DtIC=0
UNET DtMin=0
UNET MaxCRTS=0
UNET WFStab=0
UNET SFStab=0
UNET WFX=0
UNET SFX=0
UNET DSS MLevel=0
UNET DZMax Abort=0
UNET Convert EG Bridges=0
UNET Use Existing IB Tables=0
UNET Froude Limit=0
UNET Froude Power=0
Write IC File=0
Echo Input=False
Echo Output=False
Write Detailed=0

--- LLAURELRN.f01 (steady flow) ---

Flow Title=NFF Regression Equation
Program Version=5.03
Number of Profiles= 1
Profile Names=P100yr
River Rch & RM=LLAURELRN,Main            ,17246.9
522.3129
River Rch & RM=LLAURELRN,Main            ,16136.2
547.8871
River Rch & RM=LLAURELRN,Main            ,14388.6
589.3773
River Rch & RM=LLAURELRN,Main            ,13453.4
630.5626
River Rch & RM=LLAURELRN,Main            ,11118.9
710.3176
River Rch & RM=LLAURELRN,Main            ,11118.9
686.5834
River Rch & RM=LLAURELRN,Main            ,8477.2
780.4517
River Rch & RM=LLAURELRN,Main            ,6262.2
 818.221
River Rch & RM=LLAURELRN,Main            ,489.8
908.3937
River Rch & RM=LLAURELRN,Main            ,223.3
910.5131
Boundary for River Rch & Prof#=LLAURELRN,Main            , 1
Up Type= 0
Dn Type= 3
Dn Slope=0.0169
DSS Import GetInterval= 0
DSS Import GetPeak= 0
DSS Import FillOption= 0

--- LLAURELRN.g01 (geometry) ---

Geom Title=USGS 10m DEM
Program Version=4.10

River Reach=LLAURELRN       ,Main
Reach XY= 30
     1819747.425      220167.787     1819492.592      220134.366
     1819170.094      220447.896     1818985.656      221205.403
     1818473.306      221192.978      1818383.71      221432.087
      1817956.37       221509.85     1817632.116      221776.232
     1817622.901      222453.906     1817309.454      222608.201
     1817426.661      222939.006     1817260.896      222940.939
     1817287.107      223204.255     1817582.848       223364.39
      1817338.13      223981.118     1817488.439      224506.208
     1817303.952      224760.488     1817317.487      225124.858
     1817011.566      225141.889       1816917.2      225528.334
     1816497.057      225779.789     1816340.105      226535.322
     1815972.696      226394.157     1815867.426      226839.772
     1815398.781      226996.762     1815280.151      227209.108
     1815062.016      227091.013     1814792.844      227508.513
     1812760.246      228204.043     1811833.134      230012.811

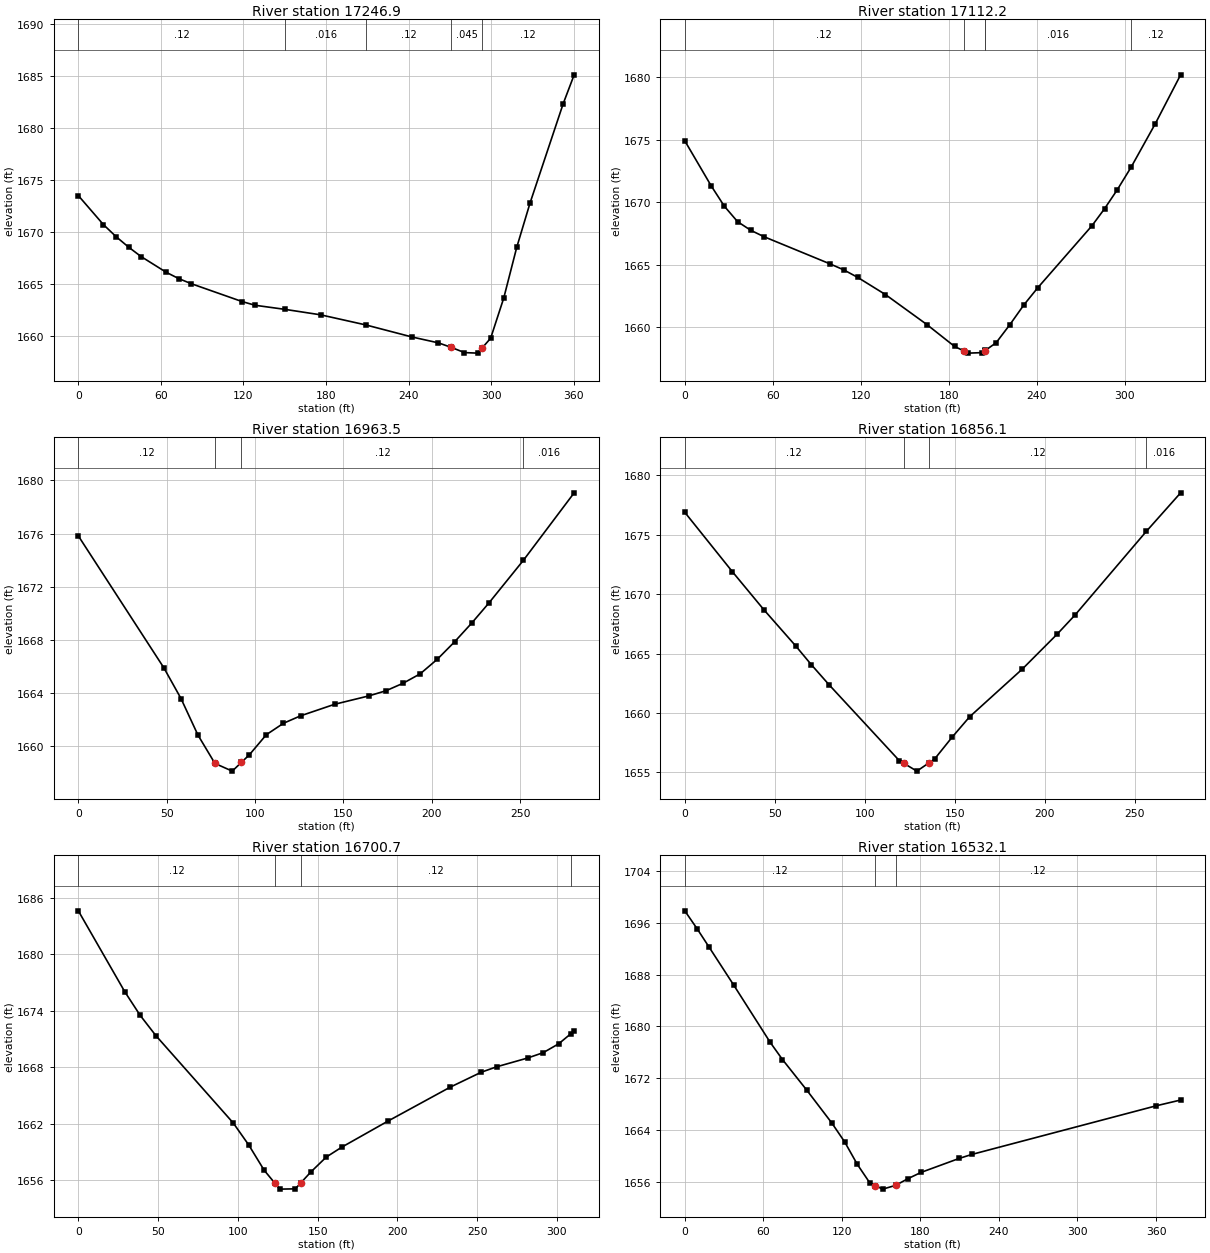
Type RM Length L Ch R = 1 ,17246.9 ,131.5,134.7,137.9
XS GIS Cut Line= 4
     1819670.716      219900.389     1819734.952      219988.931
     1819736.689      220207.681     1819749.655      220237.151
#Sta/Elev= 25
       0 1673.52    18.2 1670.73    27.4 1669.57    36.5 1668.56    45.6 1667.65
    63.8 1666.14    72.9 1665.53      82 1665.04   118.9 1663.32   128.4 1662.96
  150.481662.558     176 1662.04  208.881661.066   242.6  1659.9   261.6 1659.34
   271.1  1658.9   280.6  1658.4   290.1 1658.35  293.291658.828   299.6 1659.78
   309.1 1663.64   318.6 1668.55   328.2 1672.79   352.3 1682.36   360.3 1685.15
#Mann= 5 ,-1 , 0
       0     .12       0  150.48    .016       0  208.88     .12       0
   271.1    .045       0  293.29     .12       0
Bank Sta=271.1,293.29
XS Rating Curve= 0 ,0
Exp/Cntr=0.3,0.1

Type RM Length L Ch R = 1 ,17112.2 ,166.8,148.7,130.6
XS GIS Cut Line= 4
     1819551.927      219981.924     1819616.897      220056.639
     1819594.327      220225.042     1819627.314      220285.806
#Sta/Elev= 27
       0  1674.9      18  1671.3      27 1669.67      36 1668.44      45 1667.75
      54 1667.24      99 1665.07   108.4 1664.59   117.9 1663.99   136.8 1662.62
   165.1 1660.22     184 1658.47  190.181658.123   193.4 1657.94   202.8 1657.98
  204.37 1658.11  204.871658.151   212.3 1658.77   221.7 1660.22   231.2 1661.79
   240.6 1663.15   277.6 1668.11   286.2 1669.47   294.8 1670.97  304.28 1672.78
   320.8 1676.26   338.1 1680.17
#Mann= 5 ,-1 , 0
       0     .12       0  190.18    .045       0  204.37     .12       0
  204.87    .016       0  304.28     .12       0
Bank Sta=190.18,204.37
XS Rating Curve= 0 ,0
Exp/Cntr=0.3,0.1

Type RM Length L Ch R = 1 ,16963.5 ,110.8,107.4,104
XS GIS Cut Line= 2
      1819413.49      220088.523     1819585.647      220310.112
#Sta/Elev= 22
       0 1675.82    48.4  1665.9    58.1 1663.59    67.7 1660.84    77.3 1658.71
    87.1 1658.13    92.3 1658.79    96.8 1659.36   106.4 1660.87   116.1 1661.73
   125.8 1662.29   145.1 1663.16   164.5 1663.79   174.2 1664.18   183.8 1664.74
   193.5 1665.45   203.2 1666.55   212.9 1667.85   222.6 1669.26   232.2 1670.75
  251.841673.981   280.6 1679.06
#Mann= 4 ,-1 , 0
       0     .12       0    77.3    .045       0    92.3     .12       0
  251.84    .016       0
Bank Sta=77.3,92.3
XS Rating Curve= 0 ,0
Exp/Cntr=0.3,0.1

Type RM Length L Ch R = 1 ,16856.1 ,161.2,155.4,149.7
XS GIS Cut Line= 3
      1819356.48      220145.181     1819380.786      220211.153
     1819530.091      220351.778
#Sta/Elev= 18
       0 1676.88    26.4 1671.89    43.9 1668.69    61.5 1665.66    70.3 1664.06
    80.1 1662.38   119.1    1656  121.581655.773   128.9 1655.11  135.57  1655.8
   138.7 1656.12   148.4 1657.95   158.2 1659.68   187.5  1663.7     207 1666.66
   216.8 1668.25  256.431675.292   275.4 1678.52
#Mann= 4 ,-1 , 0
       0     .12       0  121.58    .045       0  135.57     .12       0
  256.43    .016       0
Bank Sta=121.58,135.57
XS Rating Curve= 0 ,0
Exp/Cntr=0.3,0.1

Type RM Length L Ch R = 1 ,16700.7 ,158.1,168.6,179
XS GIS Cut Line= 2
     1819182.869      220266.709     1819455.439      220416.014
#Sta/Elev= 23
       0 1684.59    29.1 1676.01    38.8 1673.49    48.6 1671.35    97.1 1662.08
   106.8 1659.75   116.5 1657.06   123.11655.711   126.3 1655.06     136 1655.09
  139.351655.705   145.7 1656.87   155.4 1658.46   165.1 1659.51   194.2 1662.29
   233.1 1665.88   252.5 1667.46   262.2 1668.04   281.6 1668.97   291.4 1669.54
   301.1 1670.48  308.511671.519   310.8 1671.84
#Mann= 4 ,-1 , 0
       0     .12       0   123.1    .045       0  139.35     .12       0
  308.51    .016       0
Bank Sta=123.1,139.35
XS Rating Curve= 0 ,0
Exp/Cntr=0.3,0.1

Type RM Length L Ch R = 1 ,16532.1 ,165.9,154.8,143.6
XS GIS Cut Line= 4
     1819064.073      220351.229     1819151.619       220404.73
     1819234.952      220524.521     1819363.756      220543.842
#Sta/Elev= 20
       0 1697.89     9.3 1695.15    18.6 1692.26    37.3 1686.42    65.3 1677.52
    74.6 1674.88    93.3 1670.11   112.3 1665.06   122.1 1662.14   131.8 1658.65
   141.4 1655.77  145.491655.373   151.2 1654.82     161  1655.4   170.7 1656.46
   180.4  1657.4   209.6 1659.57   219.3 1660.19   360.2 1667.72   378.8 1668.61
#Mann= 3 ,-1 , 0
       0     .12       0  145.49    .045       0     161     .12       0
Bank Sta=145.49,161
XS Rating Curve= 0 ,0
Exp/Cntr=0.3,0.1

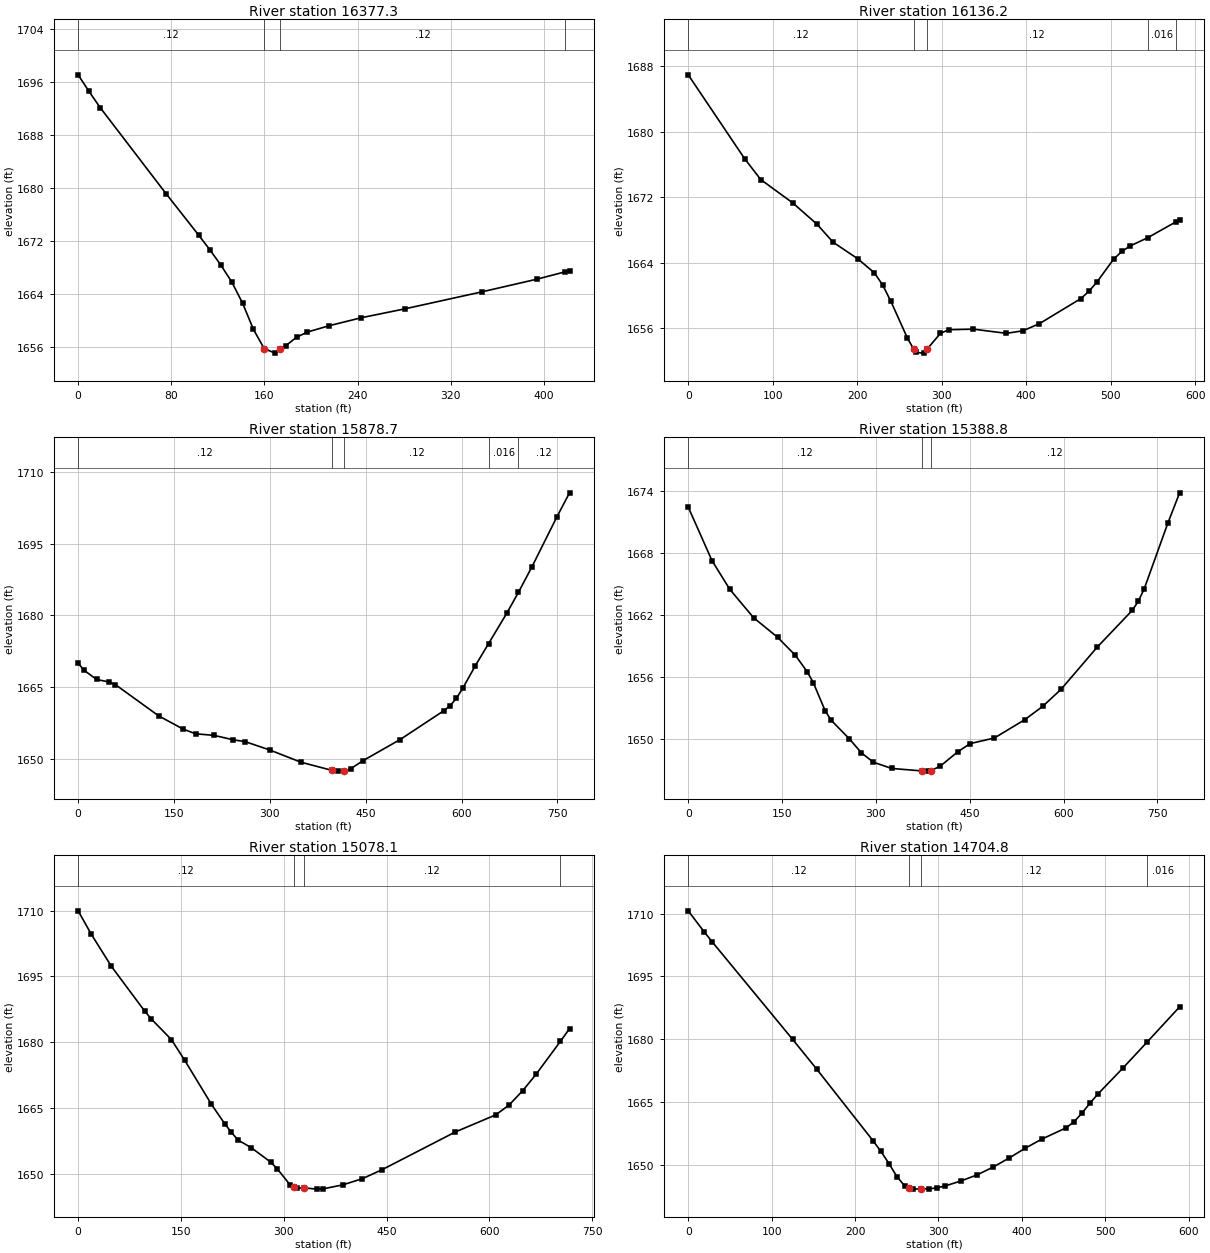
Type RM Length L Ch R = 1 ,16377.3 ,246.3,241,235.1
XS GIS Cut Line= 4
     1818969.961      220464.847     1819064.814      220556.639
     1819196.758      220624.348     1819337.324      220641.145
#Sta/Elev= 23
       0 1697.03     9.4 1694.52    18.9  1692.1    75.4 1679.13   103.7 1672.81
   113.1 1670.65   122.6 1668.32     132 1665.77   141.3 1662.56   150.5 1658.64
   159.8 1655.74   169.1 1655.06  173.76 1655.63   178.3 1656.18   187.6 1657.46
   196.9 1658.24   215.4 1659.19   243.2  1660.4   280.3 1661.73   346.4 1664.29
   393.6  1666.2  418.14 1667.32   421.9 1667.49
#Mann= 4 ,-1 , 0
       0     .12       0   159.8    .045       0  173.76     .12       0
  418.14    .016       0
Bank Sta=159.8,173.76
XS Rating Curve= 0 ,0
Exp/Cntr=0.3,0.1

Type RM Length L Ch R = 1 ,16136.2 ,255.6,257.5,259.9
XS GIS Cut Line= 3
     1818848.973      220612.036     1818915.596      220770.154
      1819315.48       220861.31
#Sta/Elev= 30
       0 1686.96    66.7 1676.72    85.8 1674.16   123.9 1671.29   152.5 1668.69
   171.6 1666.49   200.9 1664.46   220.4 1662.75   230.2 1661.26   239.9 1659.27
   259.5 1654.77   267.11653.397   269.2 1653.02     279 1652.94   282.6 1653.41
   298.5 1655.35   308.3  1655.8   337.6 1655.87   376.6 1655.36   396.2 1655.67
   415.7 1656.54   464.5 1659.59   474.3 1660.49   484.1 1661.67   503.6 1664.43
   513.4 1665.38   523.1 1666.04  543.98 1667.05  577.981669.027   581.7 1669.23
#Mann= 5 ,-1 , 0
       0     .12       0   267.1    .045       0   282.6     .12       0
  543.98    .016       0  577.98     .12       0
Bank Sta=267.1,282.6
XS Rating Curve= 0 ,0
Exp/Cntr=0.3,0.1

Type RM Length L Ch R = 1 ,15878.7 ,436.1,489.9,515.9
XS GIS Cut Line= 4
      1818695.87      220750.505     1818811.429      220984.998
     1819069.242      221069.633     1819285.411       221164.38
#Sta/Elev= 30
       0 1669.96     9.7 1668.46      29 1666.57    48.4 1666.05    58.1 1665.52
   125.9 1658.96   164.6 1656.15     184 1655.19     213 1654.86   242.1 1653.94
   261.4 1653.55   300.2 1651.78   348.6 1649.24   397.1 1647.53   406.8 1647.37
   416.5 1647.43   426.2 1647.85   445.6 1649.55   503.7 1653.98   572.1 1660.02
   581.9 1661.07   591.8 1662.62   601.6 1664.69   621.3 1669.42  642.211674.105
   670.4  1680.4  688.841684.818   709.8 1690.12   749.1 1700.65   768.8 1705.68
#Mann= 5 ,-1 , 0
       0     .12       0   397.1    .045       0   416.5     .12       0
  642.21    .016       0  688.84     .12       0
Bank Sta=397.1,416.5
XS Rating Curve= 0 ,0
Exp/Cntr=0.3,0.1

Type RM Length L Ch R = 1 ,15388.8 ,249.6,310.7,309.1
XS GIS Cut Line= 4
     1818596.916      220811.362     1818739.815      220977.185
     1818798.408      221388.643     1818782.468      221538.939
#Sta/Elev= 30
       0 1672.44    38.1 1667.24    66.6 1664.46   104.7 1661.71   142.8 1659.83
   171.3 1658.08   190.4 1656.47   199.9 1655.44   218.9 1652.71   228.6 1651.78
   257.6 1649.99   276.9 1648.63   296.2 1647.72   325.2 1647.12   373.6 1646.88
   383.2 1646.86  387.871646.916   402.5 1647.32   431.5 1648.76   450.9 1649.53
   489.5 1650.07   537.9 1651.84   566.8 1653.14   595.8 1654.77   653.4 1658.84
   710.1 1662.45   719.5 1663.31     729 1664.52   766.8 1670.89   785.6 1673.82
#Mann= 3 ,-1 , 0
       0     .12       0   373.6    .045       0  387.87     .12       0
Bank Sta=373.6,387.87
XS Rating Curve= 0 ,0
Exp/Cntr=0.3,0.1

Type RM Length L Ch R = 1 ,15078.1 ,368.7,373.3,359.4
XS GIS Cut Line= 4
     1818338.903      220990.656      1818549.71      221090.466
     1818620.023      221328.748     1818610.698      221563.733
#Sta/Elev= 30
       0 1709.96    19.4 1704.58    48.6 1697.29    97.2 1687.09   106.9 1685.29
   136.1 1680.61   155.5 1675.89   194.4 1665.88   213.8 1661.44   223.5 1659.49
   233.2 1657.72   252.4 1655.99     281 1652.68   290.6 1651.14   309.7  1647.4
  314.631647.055   319.2 1646.74   328.8 1646.84   347.9 1646.53   357.5  1646.6
   386.1  1647.5   414.8 1648.92   443.5 1650.97   550.3 1659.56   609.1 1663.45
   628.7 1665.71   648.3 1668.93   667.9 1672.68   703.61680.228   716.8  1683.1
#Mann= 4 ,-1 , 0
       0     .12       0  314.63    .045       0   328.8     .12       0
   703.6    .016       0
Bank Sta=314.63,328.8
XS Rating Curve= 0 ,0
Exp/Cntr=0.3,0.1

Type RM Length L Ch R = 1 ,14704.8 ,305.9,316.2,325.4
XS GIS Cut Line= 3
     1818190.751      221116.015     1818500.231      221432.914
     1818514.205      221578.533
#Sta/Elev= 30
       0 1710.68    19.3 1705.61    28.9 1703.22   125.2 1679.94   154.1 1672.82
   221.5 1655.73   231.1 1653.15   240.7 1650.25   250.4 1647.09     260  1644.8
  264.451644.493   269.6 1644.14   279.2 1644.22   288.9 1644.21   298.5 1644.47
   308.1  1644.9   327.4 1646.12   346.6 1647.57   365.9 1649.44   385.2 1651.63
   404.4 1653.96   423.7 1656.07   452.7 1658.76   462.4  1660.2   472.2 1662.33
     482 1664.77   491.7 1666.98     521 1673.04  549.83 1679.22   589.2 1687.72
#Mann= 4 ,-1 , 0
       0     .12       0  264.45    .045       0   279.2     .12       0
  549.83    .016       0
Bank Sta=264.45,279.2
XS Rating Curve= 0 ,0
Exp/Cntr=0.3,0.1

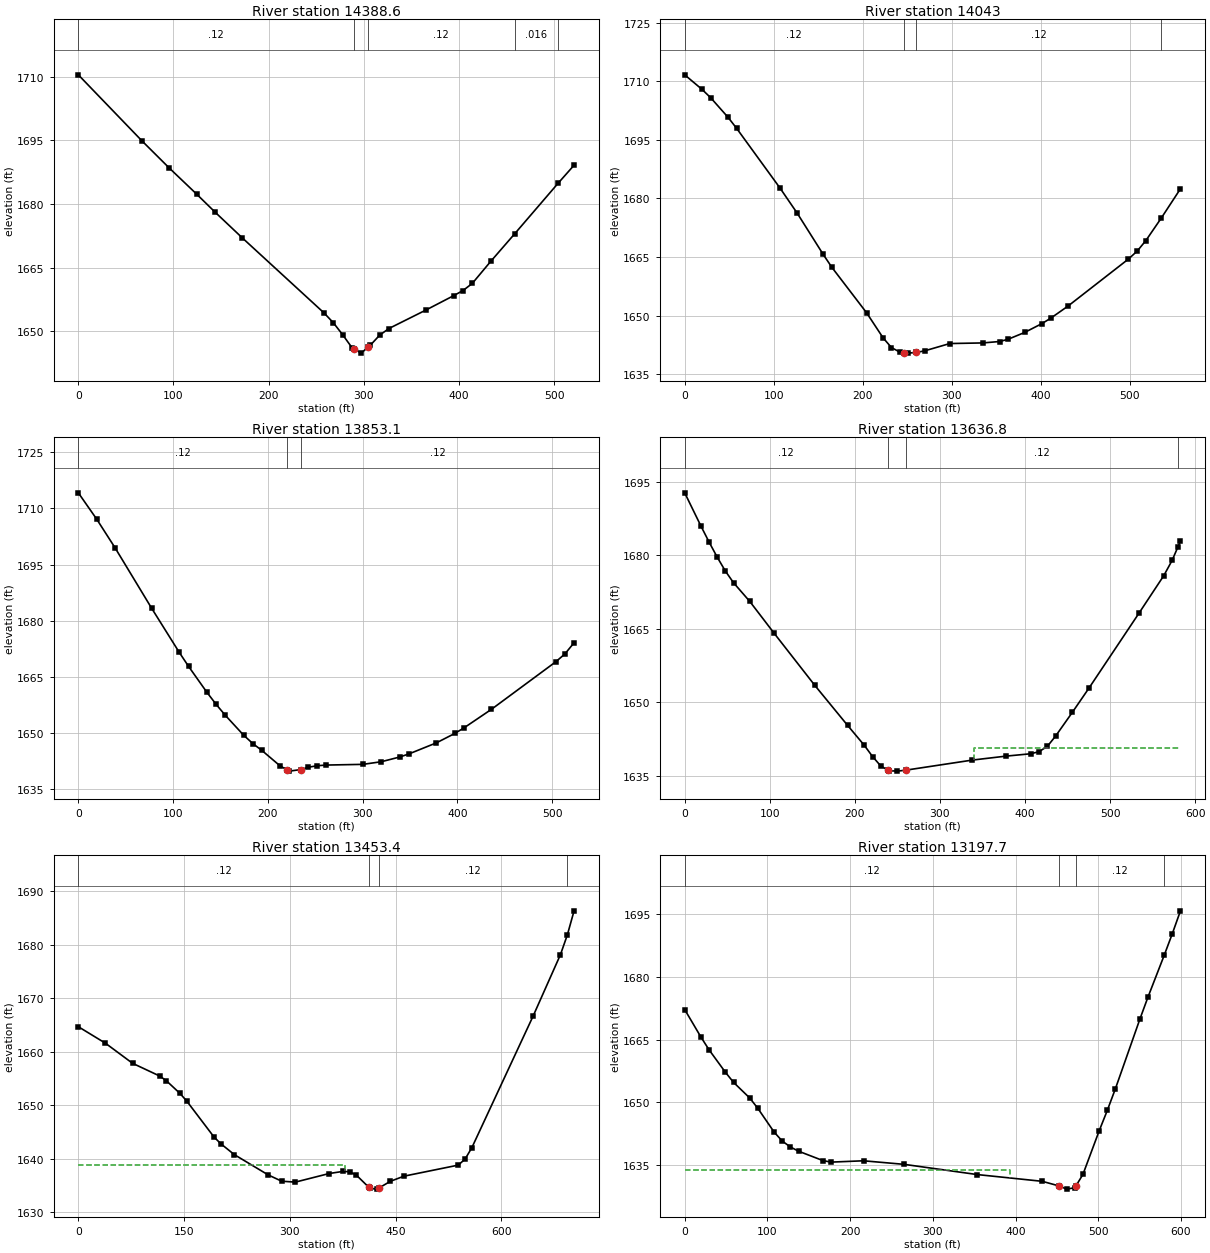
Type RM Length L Ch R = 1 ,14388.6 ,335,345.5,350.6
XS GIS Cut Line= 3
     1818070.768      221198.052     1818190.335      221415.987
     1818290.803      221669.167
#Sta/Elev= 24
       0  1710.4    66.9 1694.85    95.6 1688.46   124.3 1682.33   143.4 1678.15
   172.1 1672.07   258.3 1654.34     268 1652.05   277.8 1649.23   287.5 1646.21
   289.3 1645.97   297.2  1644.9   304.3 1646.27     307 1646.79   316.7 1649.13
   326.4 1650.69   365.3 1655.04   394.5 1658.43   404.2 1659.62     414  1661.3
   433.4 1666.49  458.541672.975   504.4 1684.93     521 1689.13
#Mann= 5 ,-1 , 0
       0     .12       0   289.3    .045       0   304.3     .12       0
  458.54    .016       0   504.4     .12       0
Bank Sta=289.3,304.3
XS Rating Curve= 0 ,0
Exp/Cntr=0.3,0.1

Type RM Length L Ch R = 1 ,14043   ,206.5,190,178.1
XS GIS Cut Line= 4
     1817902.069      221289.367     1817998.929      221469.373
     1817985.908      221646.456     1818102.289      221777.492
#Sta/Elev= 30
       0 1711.62    19.5 1707.89    29.2 1705.76    48.7 1700.76    58.4 1697.92
   107.1 1682.67   126.5 1676.22   155.7 1665.68   165.5 1662.36   204.4 1650.78
   223.1 1644.32   232.4 1641.87   241.8 1640.71  246.111640.592   251.1 1640.45
   260.5 1640.63   269.8 1641.04   297.9  1642.9   335.2 1643.06   353.9 1643.42
   363.3 1643.98     382 1645.73   401.4 1647.99   411.2 1649.35   430.7 1652.46
   498.8 1664.52   508.6 1666.55   518.3 1669.23   535.6 1674.97   557.2 1682.48
#Mann= 4 ,-1 , 0
       0     .12       0  246.11    .045       0   260.5     .12       0
   535.6    .016       0
Bank Sta=246.11,260.5
XS Rating Curve= 0 ,0
Exp/Cntr=0.3,0.1

Type RM Length L Ch R = 1 ,13853.1 ,220.4,216.3,212.1
XS GIS Cut Line= 2
     1817693.006       221415.33     1818016.119      221827.008
#Sta/Elev= 30
       0 1714.18    19.4 1707.14    38.8 1699.48    77.5 1683.29   106.6 1671.52
   116.3 1667.82   135.7 1660.88   145.4 1657.67   155.1 1654.74   174.4 1649.44
   184.1 1647.19   193.8 1645.33   213.2 1641.16   219.9 1640.23   222.9 1639.81
   234.9 1640.23   242.3 1640.82     252 1641.25   261.7 1641.43   300.4 1641.62
   319.8 1642.32   339.2 1643.58   348.9  1644.4     378 1647.37   397.4 1649.88
     407 1651.35   436.1 1656.33     504 1669.03   513.6 1671.12   523.3 1674.12
#Mann= 3 ,-1 , 0
       0     .12       0   219.9    .045       0   234.9     .12       0
Bank Sta=219.9,234.9
XS Rating Curve= 0 ,0
Exp/Cntr=0.3,0.1

Type RM Length L Ch R = 1 ,13636.8 ,207.1,183.4,159.8
XS GIS Cut Line= 3
     1817538.385      221530.337     1817621.325      221692.029
     1817922.282      221957.103
#Sta/Elev= 30
       0 1692.79    19.1 1685.99    28.7 1682.71    38.3 1679.61    47.8  1676.8
    57.4 1674.41    76.5 1670.59   105.2 1664.07     153 1653.42   191.5 1645.25
   211.1 1641.18   220.8 1638.89   230.6 1636.93  238.421636.171   240.4 1635.98
   250.1  1635.9     260  1636.1   338.2 1638.16   377.4 1638.96   406.7 1639.45
   416.5 1639.87   426.3 1640.96     436 1643.06   455.6 1647.89   475.2 1652.86
   533.9 1668.15   563.2 1675.86     573 1678.98  579.771681.709   582.8 1682.93
#Mann= 4 ,-1 , 0
       0     .12       0  238.42    .045       0     260     .12       0
  579.77    .016       0
#XS Ineff= 2 , 0
                          339.94         1640.64
Permanent Ineff=
       F       F
Bank Sta=238.42,260
XS Rating Curve= 0 ,0
Exp/Cntr=0.3,0.1

Type RM Length L Ch R = 1 ,13453.4 ,245,255.6,266.1
XS GIS Cut Line= 4
     1817324.426      221734.719     1817564.033      221927.706
     1817756.742      221866.508     1817914.192      221978.381
#Sta/Elev= 30
       0 1664.64    38.5 1661.55    76.9  1657.8   115.4 1655.42     125 1654.52
   144.2 1652.16   153.8 1650.73   192.3 1644.04   201.9 1642.78   221.1 1640.74
   269.2 1636.94   288.4 1635.76   307.7 1635.59   355.8  1637.2   375.1 1637.59
   384.7 1637.53   394.3 1636.89   411.5 1634.68   413.6 1634.42   423.2 1634.28
   426.5 1634.51   442.5 1635.74   461.7  1636.7   538.8 1638.77   548.5 1639.91
   558.1 1642.04   645.1 1666.68   683.7 1678.12  693.481681.805     703  1686.3
#Mann= 4 ,-1 , 0
       0     .12       0   411.5    .045       0   426.5     .12       0
  693.48    .016       0
#XS Ineff= 2 , 0
          378.12 1638.82
Permanent Ineff=
       F       F
Bank Sta=411.5,426.5
XS Rating Curve= 0 ,0
Exp/Cntr=0.3,0.1

Type RM Length L Ch R = 1 ,13197.7 ,340.7,338,335.3
XS GIS Cut Line= 2
     1817253.744      222061.755     1817845.024      222160.302
#Sta/Elev= 30
       0 1672.16    19.6  1665.6    29.5 1662.54    49.1 1657.23      59  1654.8
    78.6 1651.07    88.4  1648.6   108.1 1642.94   117.9  1640.8   127.8 1639.38
   137.6 1638.38   167.1 1636.14   176.9 1635.77   216.2 1636.09   265.3 1635.24
   353.8  1632.8   432.4 1631.19     452 1630.12   461.9 1629.33   471.7 1629.67
  473.111630.125   481.5 1632.84   501.2 1643.27     511 1648.13   520.8  1653.3
   550.3 1669.85   560.1 1675.11  579.721685.079   589.6 1690.27   599.4  1695.7
#Mann= 4 ,-1 , 0
       0     .12       0     452    .045       0  473.11     .12       0
  579.72    .016       0
#XS Ineff= 2 , 0
          393.19 1633.78
Permanent Ineff=
       F       F
Bank Sta=452,473.11
XS Rating Curve= 0 ,0
Exp/Cntr=0.3,0.1

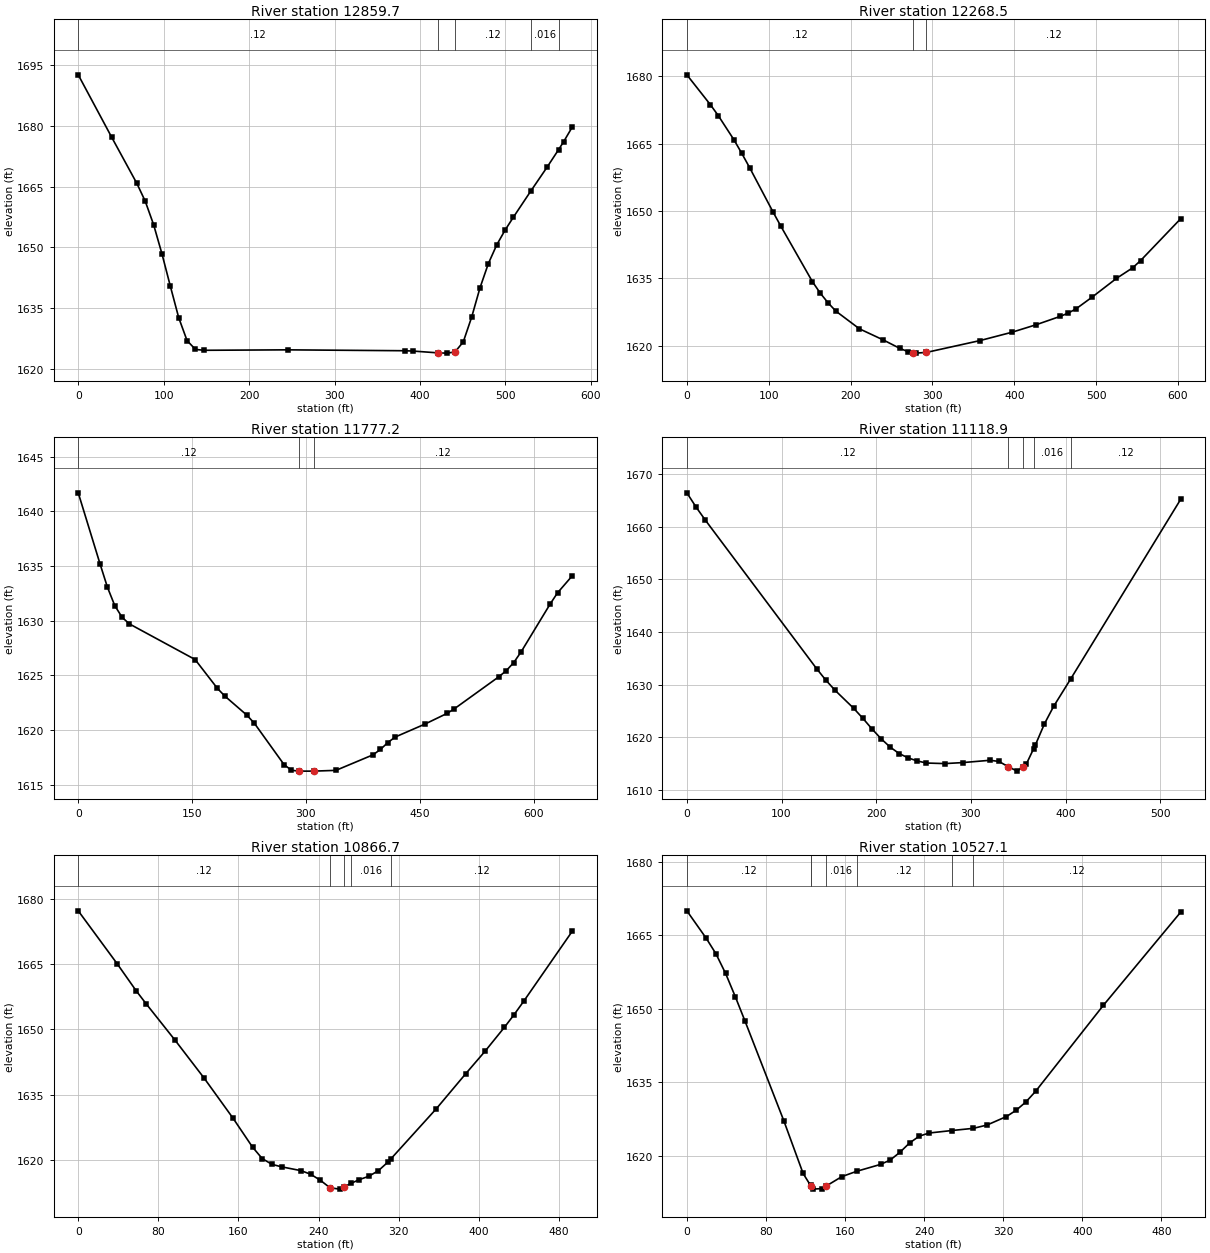
Type RM Length L Ch R = 1 ,12859.7 ,599.5,591.2,582.4
XS GIS Cut Line= 2
     1817190.161      222418.619     1817767.118      222454.913
#Sta/Elev= 29
       0 1692.55    39.2 1677.14    68.6 1665.78    78.4  1661.4    88.2 1655.62
      98 1648.41   107.8 1640.45   117.6 1632.67   127.4    1627   137.2 1624.84
     147 1624.62     245 1624.73   382.1 1624.51   391.9 1624.43   421.3 1623.98
   431.1 1623.92   440.9 1624.18   450.7 1626.68   460.5 1632.77   470.3 1640.03
   480.1 1646.01   489.9 1650.62   499.7 1654.27   509.5 1657.48  529.491663.801
   548.7 1669.74  562.381674.127   568.3 1676.09   578.1  1679.6
#Mann= 5 ,-1 , 0
       0     .12       0   421.3    .045       0   440.9     .12       0
  529.49    .016       0  562.38     .12       0
Bank Sta=421.3,440.9
XS Rating Curve= 0 ,0
Exp/Cntr=0.3,0.1

Type RM Length L Ch R = 1 ,12268.5 ,484.6,491.3,496
XS GIS Cut Line= 3
     1817138.252        222736.3     1817327.054       222830.05
      1817702.19      222714.623
#Sta/Elev= 30
       0 1680.31    28.8 1673.65    38.3 1671.25    57.5 1665.86    67.1 1662.83
    76.6 1659.68   105.4 1649.74     115 1646.56   153.3 1634.31   162.9 1631.74
   172.5 1629.57     182 1627.73   210.8 1623.79   240.2 1621.29   259.9 1619.46
   269.7 1618.74  276.081618.508   279.5 1618.38  292.581618.537     358 1621.17
   397.2 1623.03   426.7  1624.7   456.1 1626.56   465.9 1627.29   475.7 1628.27
   495.4 1630.89   524.8 1635.01   544.4 1637.34   554.2 1638.96   603.3  1648.3
#Mann= 3 ,-1 , 0
       0     .12       0  276.08    .045       0  292.58     .12       0
Bank Sta=276.08,292.58
XS Rating Curve= 0 ,0
Exp/Cntr=0.3,0.1

Type RM Length L Ch R = 1 ,11777.2 ,641.8,658.2,667.7
XS GIS Cut Line= 4
     1817137.458      223193.293      1817205.96       223055.31
      1817630.44      222988.904     1817689.978      222957.916
#Sta/Elev= 30
       0 1641.69    28.9 1635.15    38.5 1633.05    48.1 1631.38    57.8  1630.3
    67.4  1629.7     154 1626.44   183.4  1623.8   193.1  1623.1   222.4 1621.34
   232.2  1620.6   271.2 1616.83     281 1616.31   290.8 1616.23   310.3 1616.23
   339.6  1616.3   388.4 1617.72   398.2 1618.21   407.9 1618.84   417.7 1619.35
   456.8 1620.53     486 1621.51   495.8 1621.94   554.4 1624.87   564.2 1625.43
   573.9 1626.16   583.7 1627.15     622 1631.53   631.6 1632.54   650.8 1634.08
#Mann= 3 ,-1 , 0
       0     .12       0   290.8    .045       0   310.3     .12       0
Bank Sta=290.8,310.3
XS Rating Curve= 0 ,0
Exp/Cntr=0.3,0.1

Type RM Length L Ch R = 1 ,11118.9 ,253,252.2,251.5
XS GIS Cut Line= 3
     1817241.117      223438.123     1817414.294      223405.571
     1817750.391      223485.148
#Sta/Elev= 29
       0 1666.43     9.8  1663.7    19.6 1661.22     137 1633.03   146.8 1630.84
   156.6  1628.9   176.2 1625.49   185.8 1623.61   195.4  1621.6     205 1619.74
   214.6 1618.14   224.2  1616.9   233.8 1616.07   243.4 1615.49     253  1615.1
   272.2 1614.99   291.3 1615.18   320.1 1615.62   329.7  1615.4   339.3  1614.4
   348.9 1613.56  354.671614.357   358.5 1614.89  366.311617.851   368.1 1618.53
   377.7 1622.56   387.3 1625.84   405.51631.109   521.6 1665.21
#Mann= 5 ,-1 , 0
       0     .12       0   339.3    .045       0  354.67     .12       0
  366.31    .016       0   405.5     .12       0
Bank Sta=339.3,354.67
XS Rating Curve= 0 ,0
Exp/Cntr=0.3,0.1

Type RM Length L Ch R = 1 ,10866.7 ,341.9,339.6,337.2
XS GIS Cut Line= 2
     1817238.513      223625.623     1817721.389      223725.347
#Sta/Elev= 30
       0 1677.34    38.7  1665.2      58 1658.87    67.7 1655.95    96.7 1647.52
   125.7 1638.79   154.7 1629.51     174  1622.9   183.7 1620.25   193.4 1618.92
     203 1618.35   222.4 1617.47     232 1616.65   241.7 1615.26   251.4 1613.52
     261 1613.21  265.361613.728  272.671614.567   280.4 1615.38     290 1616.16
   299.7 1617.46   309.4 1619.48  312.051620.151   357.7 1631.78   386.7 1639.75
     406 1644.93   425.4 1650.46   435.1 1653.39   444.7 1656.47   493.1 1672.58
#Mann= 5 ,-1 , 0
       0     .12       0   251.4    .045       0  265.36     .12       0
  272.67    .016       0  312.05     .12       0
Bank Sta=251.4,265.36
XS Rating Curve= 0 ,0
Exp/Cntr=0.3,0.1

Type RM Length L Ch R = 1 ,10527.1 ,343.6,343.5,343.3
XS GIS Cut Line= 2
     1817210.575      223949.945     1817708.349        223992.8
#Sta/Elev= 30
       0 1670.04    19.6 1664.43    29.4 1661.27    39.2 1657.24      49  1652.5
    58.8 1647.52      98 1627.19   117.6 1616.38  125.131613.923  125.191613.903
   127.4 1613.18   137.2  1613.3  141.151613.837   156.7 1615.73   171.71616.818
   195.9 1618.23   205.7 1619.12   215.5  1620.7   225.3 1622.61   235.1    1624
   244.9 1624.64  267.851625.148  289.931625.603   303.7 1626.28   323.3 1628.01
   333.1 1629.29   342.9 1630.98   352.7 1633.14   421.2  1650.7   499.6 1669.78
#Mann= 7 ,-1 , 0
       0     .12       0  125.13    .016       0  125.19    .045       0
  141.15    .016       0   171.7     .12       0  267.85     .06       0
  289.93     .12       0
Bank Sta=125.19,141.15
XS Rating Curve= 0 ,0
Exp/Cntr=0.3,0.1

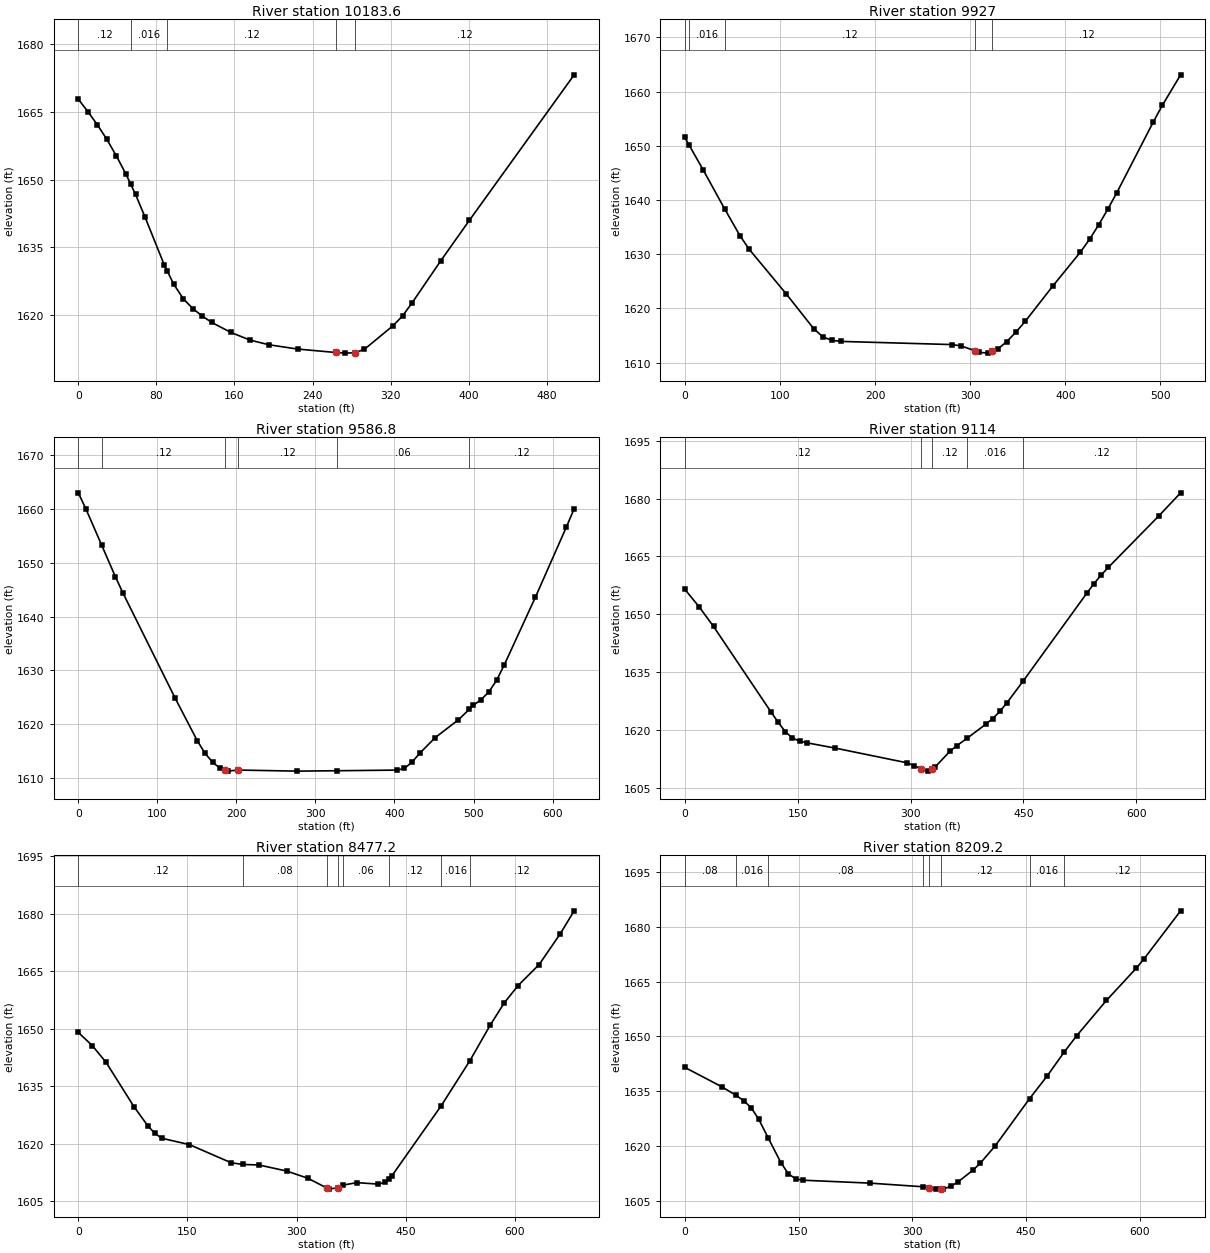
Type RM Length L Ch R = 1 ,10183.6 ,256.7,256.6,255.7
XS GIS Cut Line= 2
     1817193.356      224231.379     1817700.107      224268.673
#Sta/Elev= 30
       0 1667.81     9.8 1665.07    19.5 1662.15    29.3 1658.89    39.1  1655.2
    48.9 1651.18   53.76 1648.95    58.6 1646.73    68.4 1641.67    87.9 1631.18
    91.11629.763    97.7 1626.84   107.5 1623.61   117.3 1621.42     127 1619.76
   136.8 1618.34   156.4 1616.13   175.9 1614.44   195.4  1613.4   224.8 1612.45
   263.8 1611.69   273.6 1611.55   283.41611.635   293.2  1612.4   322.5 1617.63
   332.2 1619.78     342 1622.68   371.3 1631.98   400.6 1640.94   508.1 1673.22
#Mann= 5 ,-1 , 0
       0     .12       0   53.76    .016       0    91.1     .12       0
   263.8    .045       0   283.4     .12       0
Bank Sta=263.8,283.4
XS Rating Curve= 0 ,0
Exp/Cntr=0.3,0.1

Type RM Length L Ch R = 1 ,9927    ,339.6,340.2,334.2
XS GIS Cut Line= 3
     1817175.111       224480.74      1817580.96      224500.623
     1817691.963      224470.767
#Sta/Elev= 30
       0 1651.55    4.391650.183    19.4 1645.53   41.931638.354      58 1633.42
    67.7 1630.91   106.4 1622.73   135.4 1616.29   145.1 1614.75   154.8  1614.1
   164.5 1613.91   280.6 1613.33   290.2  1613.1  304.981612.201   309.6 1611.89
   319.3 1611.75  323.311612.055   328.9 1612.48   338.6 1613.89   348.3 1615.66
     358 1617.63     387 1624.15   415.9 1630.38   425.5 1632.74   435.1  1635.4
   444.6 1638.27   454.2 1641.35   492.6 1654.41   502.1 1657.48   521.3  1663.1
#Mann= 5 ,-1 , 0
       0     .12       0    4.39    .016       0   41.93     .12       0
  304.98    .045       0  323.31     .12       0
Bank Sta=304.98,323.31
XS Rating Curve= 0 ,0
Exp/Cntr=0.3,0.1

Type RM Length L Ch R = 1 ,9586.8  ,451.8,472.7,495.8
XS GIS Cut Line= 4
     1817124.213      224708.998     1817256.308      224758.001
     1817614.381      224782.741     1817731.283       224731.82
#Sta/Elev= 30
       0 1662.95     9.4 1660.02   29.661653.201      47 1647.35    56.4 1644.38
   122.1 1624.98   150.6 1616.94   160.3 1614.64     170 1612.95   179.7 1611.83
     186 1611.52   189.4 1611.35  202.631611.529   276.7 1611.33  326.841611.402
   402.8 1611.52   412.5 1611.82   422.2 1613.01   431.9 1614.64   451.3 1617.52
   480.4  1620.8  494.841622.824   499.8 1623.54   509.6  1624.6   519.4 1626.03
   529.2 1628.18     539 1631.07   578.3  1643.6   617.5 1656.62   627.3    1660
#Mann= 6 ,-1 , 0
       0    .016       0   29.66     .12       0     186    .045       0
  202.63     .12       0  326.84     .06       0  494.84     .12       0
Bank Sta=186,202.63
XS Rating Curve= 0 ,0
Exp/Cntr=0.3,0.1

Type RM Length L Ch R = 1 ,9114    ,636.1,636.9,630.2
XS GIS Cut Line= 4
     1817009.346      224953.128     1817147.085      225055.588
     1817314.033      225224.581     1817459.646      225427.556
#Sta/Elev= 30
       0  1656.5    19.1 1651.95    38.2 1646.88   114.4  1624.8     124  1622.1
   133.5 1619.66   143.1 1617.99   152.6 1617.18   162.1 1616.77   200.2 1615.38
   295.2 1611.59   304.7 1610.87   314.2 1610.01   323.7 1609.43  328.651610.036
   333.2 1610.59   352.2 1614.54   361.7 1616.04  375.381617.964   399.7 1621.52
   409.2 1623.04   418.8 1624.89   428.4 1627.19  449.991632.821   534.1 1655.44
   543.7 1657.94   553.3 1660.18   562.9 1662.17   630.2 1675.54     659 1681.48
#Mann= 5 ,-1 , 0
       0     .12       0   314.2    .045       0  328.65     .12       0
  375.38    .016       0  449.99     .12       0
Bank Sta=314.2,328.65
XS Rating Curve= 0 ,0
Exp/Cntr=0.3,0.1

Type RM Length L Ch R = 1 ,8477.2  ,269.8,268,266.5
XS GIS Cut Line= 3
     1816778.411      225113.018      1816880.44      225339.164
     1817191.251      225641.096
#Sta/Elev= 30
       0 1649.04    19.1 1645.64    38.2 1641.24    76.3 1629.74    95.4 1624.74
     105 1622.78   114.5 1621.48   152.7 1619.81   209.9 1615.09  225.88 1614.64
   248.1 1614.51   286.6 1612.91   315.5 1611.04   341.5  1608.5   344.4 1608.21
   356.5 1608.57   364.31609.283   382.9  1609.9   411.8 1609.52   421.4 1609.96
  426.451610.875     431  1611.7  498.771629.965  538.061641.672   565.9 1650.91
   585.1  1656.7   604.4 1661.28   633.3 1666.75   662.2 1674.74   681.4 1680.75
#Mann= 8 ,-1 , 0
       0     .12       0  225.88     .08       0   341.5    .045       0
   356.5     .12       0   364.3     .06       0  426.45     .12       0
  498.77    .016       0  538.06     .12       0
Bank Sta=341.5,356.5
XS Rating Curve= 0 ,0
Exp/Cntr=0.3,0.1

Type RM Length L Ch R = 1 ,8209.2  ,317.9,309.9,301
XS GIS Cut Line= 3
     1816550.207      225356.997     1816858.304      225641.248
     1817055.838      225768.396
#Sta/Elev= 30
       0 1641.48    48.7 1636.18    67.21633.863      78 1632.31    87.7 1630.38
    97.5 1627.28  110.29 1622.04   126.7  1615.4   136.5 1612.35   146.2 1610.93
     156 1610.56   243.7 1609.77  313.591608.778   321.7 1608.46   331.4 1608.12
  337.731608.146   341.2 1608.16     351  1608.9   360.7 1610.14   380.2 1613.32
     390 1615.28   409.4 1619.95  454.921632.938   477.9 1639.09  500.541645.692
   517.1 1650.18   556.2 1659.82   595.4 1668.62   605.2 1671.05   654.1 1684.38
#Mann= 8 ,-1 , 0
       0     .08       0    67.2    .016       0  110.29     .08       0
  313.59     .12       0   321.7    .045       0  337.73     .12       0
  454.92    .016       0  500.54     .12       0
Bank Sta=321.7,337.73
XS Rating Curve= 0 ,0
Exp/Cntr=0.3,0.1