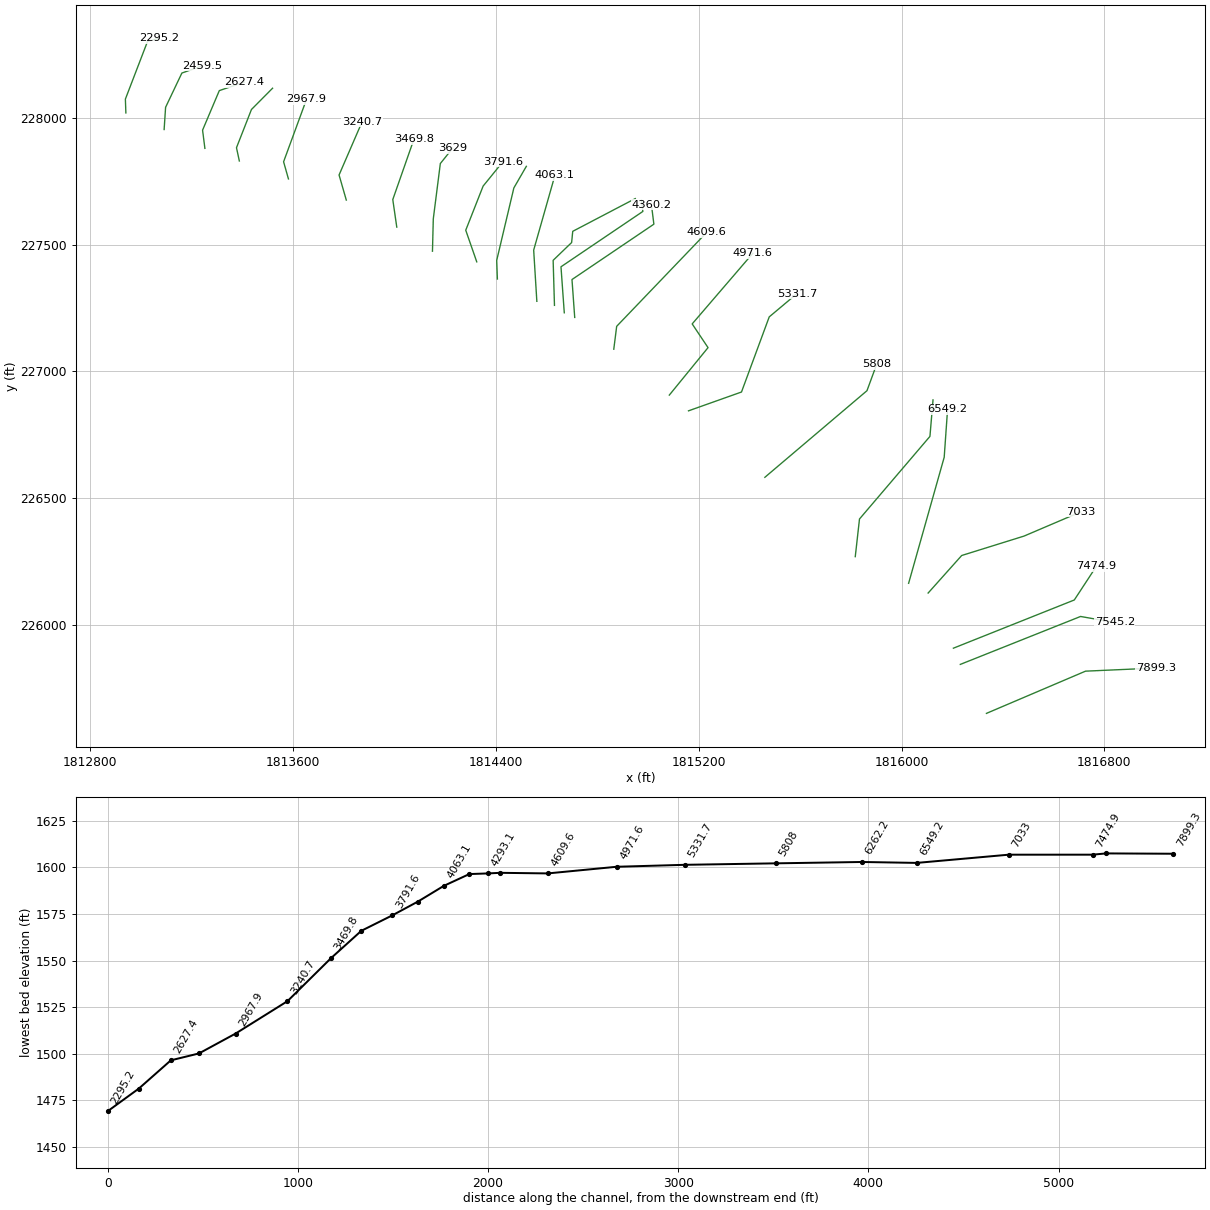
HEC-RAS study LLAURELRN.prj: LLAURELRN

--- LLAURELRN.g01 (geometry) --- (continued)

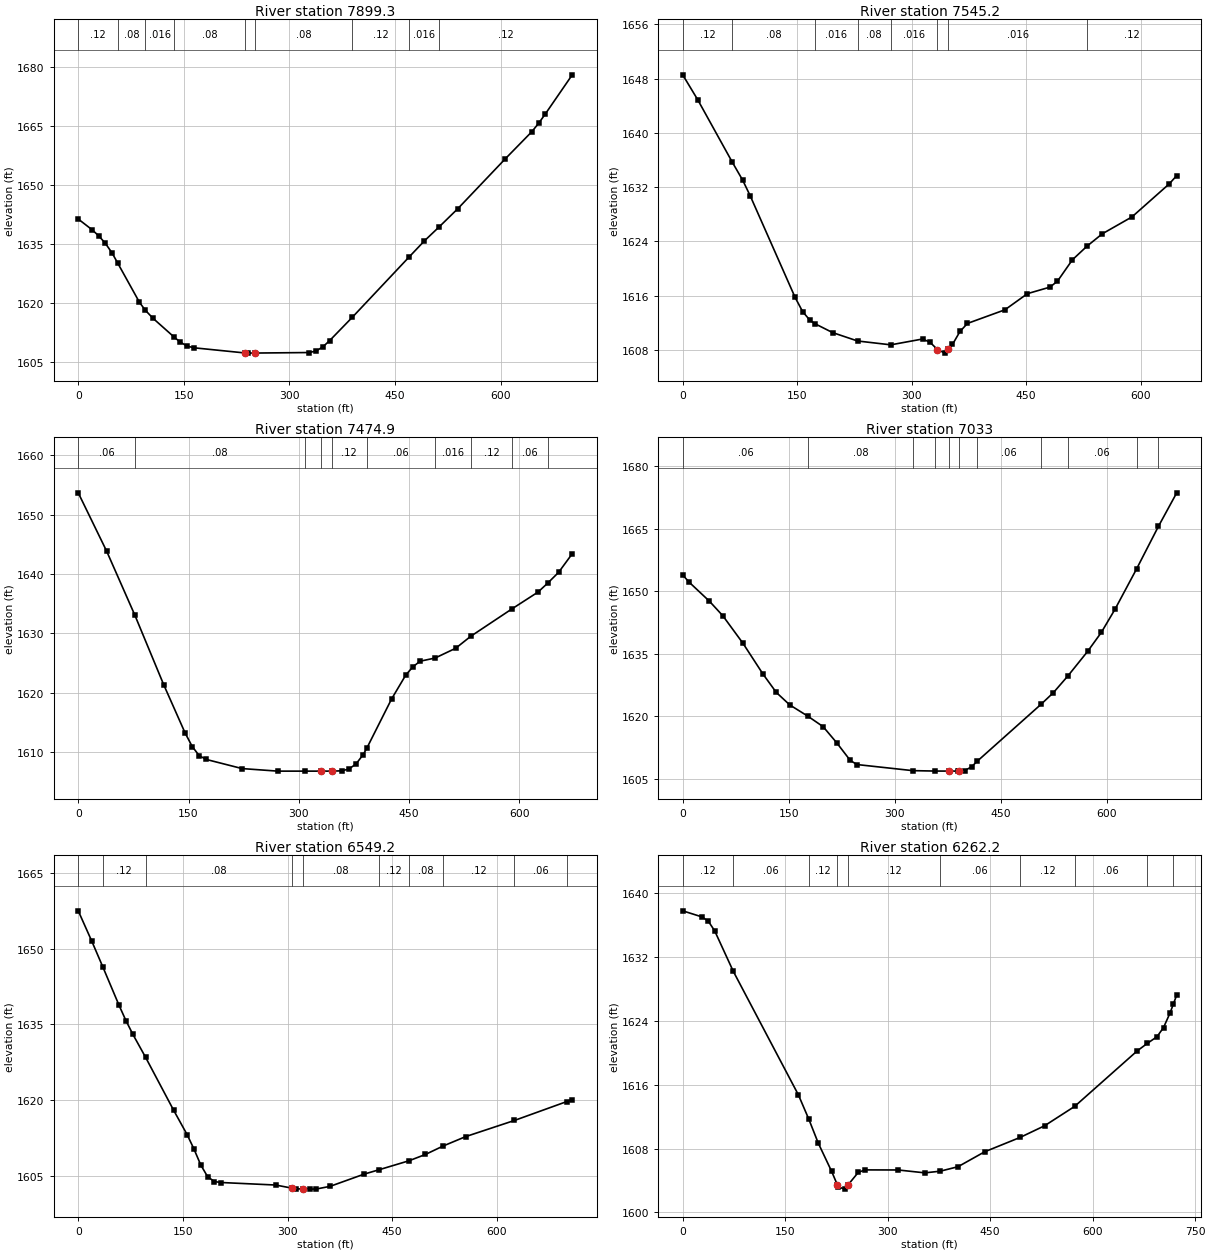
Type RM Length L Ch R = 1 ,7899.3  ,353.7,354.1,346
XS GIS Cut Line= 3
     1816334.863      225648.929     1816725.492      225815.727
     1817002.232      225828.101
#Sta/Elev= 30
       0 1641.39    19.3 1638.72      29 1637.14    38.6 1635.21    48.3  1632.7
   56.321630.119    86.9 1620.26   95.161618.247   106.2 1616.18  136.71 1611.33
   144.8 1610.15   154.4 1609.13   164.1 1608.69   236.4 1607.38   241.3 1607.33
   251.4 1607.35   328.2 1607.48   337.9 1607.87   347.5 1608.92   357.2 1610.52
  389.511616.466  469.391631.628   491.6 1635.81  513.121639.466   539.4 1644.05
   606.2  1656.6   644.4 1663.58     654  1665.7   663.6 1668.09   701.8 1678.02
#Mann= 9 ,-1 , 0
       0     .12       0   56.32     .08       0   95.16    .016       0
  136.71     .08       0   236.4    .045       0   251.4     .08       0
  389.51     .12       0  469.39    .016       0  513.12     .12       0
Bank Sta=236.4,251.4
XS Rating Curve= 0 ,0
Exp/Cntr=0.3,0.1

Type RM Length L Ch R = 1 ,7545.2  ,70.5,70.3,70.3
XS GIS Cut Line= 3
     1816231.802      225842.457      1816705.96      226031.873
      1816840.61      226008.111
#Sta/Elev= 30
       0 1648.55    19.6 1644.89   65.091635.644    78.6 1633.01    88.4 1630.72
   147.3 1615.72   157.1 1613.64   166.9 1612.33  173.761611.819   196.4 1610.54
   229.1  1609.3  272.681608.733   314.2 1609.59     324 1609.12   333.8 1608.04
   343.7 1607.51   347.91608.059   353.5 1608.79   363.3  1610.7   373.1 1611.89
   422.2  1613.9   451.7 1616.28   481.1 1617.24     491 1618.11   510.6 1621.27
  529.611623.268   549.7  1625.1   588.7  1627.6   637.6 1632.48   647.3 1633.69
#Mann= 8 ,-1 , 0
       0     .12       0   65.09     .08       0  173.76    .016       0
   229.1     .08       0  272.68    .016       0   333.8    .045       0
   347.9    .016       0  529.61     .12       0
Bank Sta=333.8,347.9
XS Rating Curve= 0 ,0
Exp/Cntr=0.3,0.1

Type RM Length L Ch R = 1 ,7474.9  ,439.6,441.9,435.8
XS GIS Cut Line= 3
     1816204.564      225906.563     1816681.221      226096.977
      1816768.01      226229.631
#Sta/Elev= 30
       0 1653.67    38.7 1643.83   76.941633.093   116.2 1621.38   145.3 1613.26
     155 1610.97   164.6 1609.42   174.3 1608.79   222.8 1607.26   271.2 1606.83
  308.47 1606.83   329.7 1606.83   344.7 1606.83   358.3 1606.88     368 1607.18
   377.7 1608.03   387.4 1609.59  392.691610.757   426.1 1618.97   445.5 1623.02
   455.2  1624.4   464.9 1625.33  485.221625.862   513.3 1627.51  533.71 1629.52
  590.161634.165   625.2 1636.96  638.441638.472   653.2 1640.28   671.8 1643.42
#Mann= 10 ,-1 , 0
       0     .06       0   76.94     .08       0  308.47     .12       0
   329.7    .045       0   344.7     .12       0  392.69     .06       0
  485.22    .016       0  533.71     .12       0  590.16     .06       0
  638.44     .12       0
Bank Sta=329.7,344.7
XS Rating Curve= 0 ,0
Exp/Cntr=0.3,0.1

Type RM Length L Ch R = 1 ,7033    ,459.1,483.8,506.8
XS GIS Cut Line= 4
     1816104.953      226124.502      1816237.21      226272.758
     1816483.304      226349.581      1816706.18      226444.946
#Sta/Elev= 30
       0 1653.86     9.5 1652.08    37.8 1647.58    56.8 1644.08    85.2  1637.5
   113.5 1630.12   132.4  1625.7   151.4 1622.71  177.271619.973   198.7 1617.48
   217.8 1613.64   236.9 1609.42   246.4  1608.4  325.431606.937  356.541606.839
   376.1 1606.83   389.6 1606.82   391.1 1606.84   399.2 1606.96   408.7 1607.87
  416.531609.175  506.69 1622.81   524.4 1625.64  544.521629.567   572.8 1635.53
   592.2 1640.08   611.6 1645.65  642.051655.304  672.941665.507   698.9 1673.58
#Mann= 11 ,-1 , 0
       0     .06       0  177.27     .08       0  325.43     .08       0
  356.54     .12       0   376.1    .045       0   391.1     .12       0
  416.53     .06       0  506.69    .016       0  544.52     .06       0
  642.05     .12       0  672.94     .06       0
Bank Sta=376.1,391.1
XS Rating Curve= 0 ,0
Exp/Cntr=0.3,0.1

Type RM Length L Ch R = 1 ,6549.2  ,297.1,287,276.5
XS GIS Cut Line= 3
     1816027.962      226162.997       1816168.2      226660.779
     1816181.668      226851.254
#Sta/Elev= 30
       0  1657.5    19.5 1651.46   35.451646.331    58.6 1638.76    68.3 1635.79
    78.1  1633.1   96.421628.531   136.6 1618.06   156.1 1613.19   165.9 1610.34
   175.6  1607.2   185.4 1604.88   195.2  1603.9   204.9 1603.72     283 1603.22
  306.861602.593   312.2 1602.44     322 1602.48   331.8 1602.41   341.5 1602.44
     361 1602.96   409.8 1605.38  431.421606.257   474.21608.029   497.6 1609.27
  522.881610.935   555.4 1612.81  625.261616.005  700.351619.747   708.1 1620.13
#Mann= 10 ,-1 , 0
       0     .06       0   35.45     .12       0   96.42     .08       0
  306.86    .045       0     322     .08       0  431.42     .12       0
   474.2     .08       0  522.88     .12       0  625.26     .06       0
  700.35    .016       0
Bank Sta=306.86,322
XS Rating Curve= 0 ,0
Exp/Cntr=0.3,0.1

Type RM Length L Ch R = 1 ,6262.2  ,458.6,454.2,448.8
XS GIS Cut Line= 4
     1815817.563      226268.196     1815834.258      226417.056
     1816112.036      226743.445     1816124.165      226887.644
#Sta/Elev= 30
       0 1637.79    28.1 1637.03    37.4  1636.5    46.8 1635.28   73.941630.223
   169.3 1614.73  184.51 1611.69   198.5 1608.66     218 1605.13  226.561603.408
   227.7 1603.18   237.5 1602.91  241.841603.427   256.9    1605   266.7 1605.32
   315.4 1605.31   354.4 1604.95  376.941605.158     403 1605.72     442 1607.59
  493.931609.392   529.7 1610.85  573.74 1613.28   665.2 1620.23  679.821621.162
   694.2 1622.01   703.8 1623.16   713.4    1625  718.171626.102   723.1 1627.24
#Mann= 10 ,-1 , 0
       0     .12       0   73.94     .06       0  184.51     .12       0
  226.56    .045       0  241.84     .12       0  376.94     .06       0
  493.93     .12       0  573.74     .06       0  679.82    .016       0
  718.17     .12       0
Bank Sta=226.56,241.84
XS Rating Curve= 0 ,0
Exp/Cntr=0.3,0.1

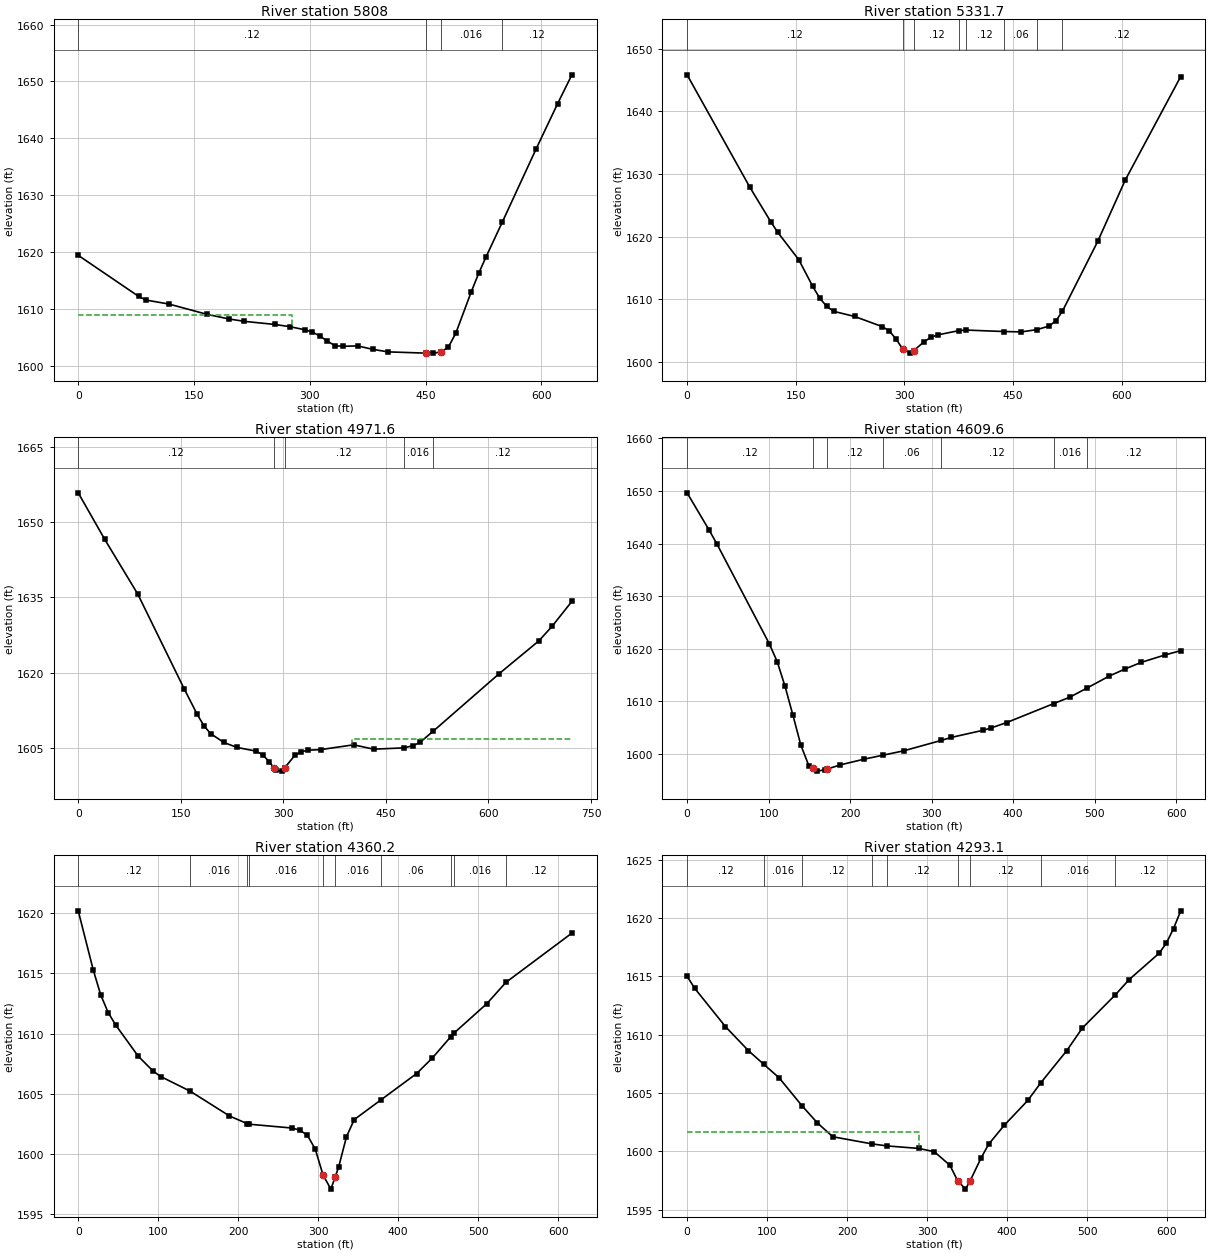
Type RM Length L Ch R = 1 ,5808    ,463.5,476.3,488.8
XS GIS Cut Line= 3
     1815461.123      226581.749     1815863.772         226924.
     1815902.013      227028.296
#Sta/Elev= 30
       0 1619.39    78.3 1612.16    88.1 1611.51   117.4 1610.82   166.4 1609.02
   195.7 1608.18   215.3 1607.77   254.4 1607.23     274 1606.84   293.6 1606.29
   303.4 1605.87   313.2 1605.19   322.9 1604.27   332.7 1603.49   342.5 1603.38
   362.1 1603.45   381.7 1602.84   401.2  1602.4   450.2 1602.18     460  1602.2
   469.7 1602.35   479.5 1603.23   489.3 1605.74   508.9 1612.88   518.7  1616.2
   528.4 1619.14  549.231625.194   593.2 1638.12     621 1646.07   639.5 1651.15
#Mann= 4 ,-1 , 0
       0     .12       0   450.2    .045       0   469.7    .016       0
  549.23     .12       0
#XS Ineff= 2 , 0
          276.68 1608.82
Permanent Ineff=
       F       F
Bank Sta=450.2,469.7
XS Rating Curve= 0 ,0
Exp/Cntr=0.3,0.1

Type RM Length L Ch R = 1 ,5331.7  ,338.4,360.1,381.5
XS GIS Cut Line= 4
      1815160.08      226844.438      1815368.98      226918.792
     1815478.355      227215.667     1815588.094      227307.848
#Sta/Elev= 30
       0 1645.83    86.8 1627.85   115.7 1622.33   125.3 1620.66   154.2  1616.3
   173.5 1612.03   183.2 1610.15   192.8 1608.85   202.5 1608.06   231.3 1607.24
   269.7 1605.61   279.3 1604.92   288.8 1603.58     298 1601.98     308 1601.39
     313  1601.8   327.2 1603.22   336.8 1603.93   346.4 1604.31   375.71604.995
  385.391605.072  437.881604.836   461.4 1604.78  483.27 1605.15   499.8 1605.72
   509.4 1606.59  518.031608.073   566.8 1619.23     605 1629.07   681.4 1645.56
#Mann= 8 ,-1 , 0
       0     .12       0     298    .045       0     313     .12       0
   375.7     .06       0  385.39     .12       0  437.88     .06       0
  483.27    .016       0  518.03     .12       0
Bank Sta=298,313
XS Rating Curve= 0 ,0
Exp/Cntr=0.3,0.1

Type RM Length L Ch R = 1 ,4971.6  ,392.6,362.1,331.5
XS GIS Cut Line= 4
     1815084.317       226906.59     1815237.036      227094.139
     1815174.536      227187.889     1815413.698      227466.912
#Sta/Elev= 30
       0 1655.85    38.7 1646.58    87.1 1635.65   154.8  1616.8   174.1 1611.64
   183.8  1609.4   193.5 1607.84   212.8 1606.07   232.2 1605.06   260.6 1604.32
     270 1603.55   279.4 1602.22   286.7 1600.88   288.8 1600.49   298.2 1600.34
   301.7 1600.95     317 1603.52   326.4  1604.2   335.8 1604.51   354.5 1604.63
   402.9 1605.59   431.9 1604.72  476.211604.976   489.9 1605.42   499.6 1606.06
  518.761608.253   615.6 1619.77   673.7 1626.32     693 1629.22     722  1634.2
#Mann= 5 ,-1 , 0
       0     .12       0   286.7    .045       0   301.7     .12       0
  476.21    .016       0  518.76     .12       0
#XS Ineff= 2 , 0
                          400.41         1606.79
Permanent Ineff=
       F       F
Bank Sta=286.7,301.7
XS Rating Curve= 0 ,0
Exp/Cntr=0.3,0.1

Type RM Length L Ch R = 1 ,4609.6  ,254,249.4,244.3
XS GIS Cut Line= 3
      1814865.39      227087.996     1814876.793      227178.341
     1815232.431      227550.144
#Sta/Elev= 30
       0 1649.63    27.3 1642.49    36.4 1639.97   100.8 1620.98   110.5 1617.59
   120.2 1612.87   129.9 1607.36   139.6 1601.68   149.3 1597.83  154.221597.293
     159 1596.77   168.7    1597  171.211597.132   188.1 1597.96   217.3 1599.05
  239.82 1599.78   265.8 1600.63  311.681602.597     324 1603.17   362.9 1604.52
   372.6 1604.95     392 1605.99  449.521609.579   469.7 1610.83  490.411612.535
   518.2 1614.85   537.6 1616.19     557 1617.42   586.2 1618.83   605.6 1619.65
#Mann= 7 ,-1 , 0
       0     .12       0  154.22    .045       0  171.21     .12       0
  239.82     .06       0  311.68     .12       0  449.52    .016       0
  490.41     .12       0
Bank Sta=154.22,171.21
XS Rating Curve= 0 ,0
Exp/Cntr=0.3,0.1

Type RM Length L Ch R = 1 ,4360.2  ,71.8,67.1,66.9
XS GIS Cut Line= 4
     1814711.335       227213.52     1814700.577      227363.237
     1815023.494      227581.987     1815013.879       227658.43
#Sta/Elev= 30
       0 1620.18    18.8 1615.27    28.1 1613.21    37.5 1611.73    46.9  1610.7
      75 1608.12    93.8 1606.87   103.2 1606.43   140.11605.212   189.1 1603.16
  211.64 1602.51  213.731602.476   267.1 1602.16   276.9 1601.99   286.6 1601.55
   296.4  1600.4   306.1 1598.26   315.9 1597.09  321.421598.131   325.6 1598.92
   335.4 1601.44   345.1 1602.86  378.441604.492   423.1 1606.68   442.6 1607.96
  465.731609.728  469.511610.017   510.9 1612.48  534.741614.245   617.2 1618.33
#Mann= 10 ,-1 , 0
       0     .12       0   140.1    .016       0  211.64     .06       0
  213.73    .016       0   306.1    .045       0  321.42    .016       0
  378.44     .06       0  465.73     .12       0  469.51    .016       0
  534.74     .12       0
Bank Sta=306.1,321.42
XS Rating Curve= 0 ,0
Exp/Cntr=0.3,0.1

Type RM Length L Ch R = 1 ,4293.1  ,80.1,96,116.3
XS GIS Cut Line= 4
     1814670.234      227231.848     1814657.175      227413.584
     1814980.091      227632.334      1814974.49      227676.864
#Sta/Elev= 30
       0 1615.01     9.6 1613.97      48 1610.69    76.7 1608.63   96.081607.449
   115.1  1606.3  143.521603.915     163 1602.43   182.2 1601.25  230.641600.643
  249.811600.466   289.5 1600.25     309 1599.97   328.5 1598.81   338.2 1597.49
     348 1596.76  353.791597.461   367.5 1599.43   377.2 1600.63   396.7 1602.25
     426 1604.37  442.131605.873   474.7 1608.64   494.2 1610.58  535.041613.395
   552.7 1614.73   590.2 1616.99   599.2 1617.86   608.1  1619.1   617.1 1620.62
#Mann= 9 ,-1 , 0
       0     .12       0   96.08    .016       0  143.52     .12       0
  230.64     .08       0  249.81     .12       0   338.2    .045       0
  353.79     .12       0  442.13    .016       0  535.04     .12       0
#XS Ineff= 2 , 0
          289.68 1601.64
Permanent Ineff=
       F       F
Bank Sta=338.2,353.79
XS Rating Curve= 0 ,0
Exp/Cntr=0.3,0.1

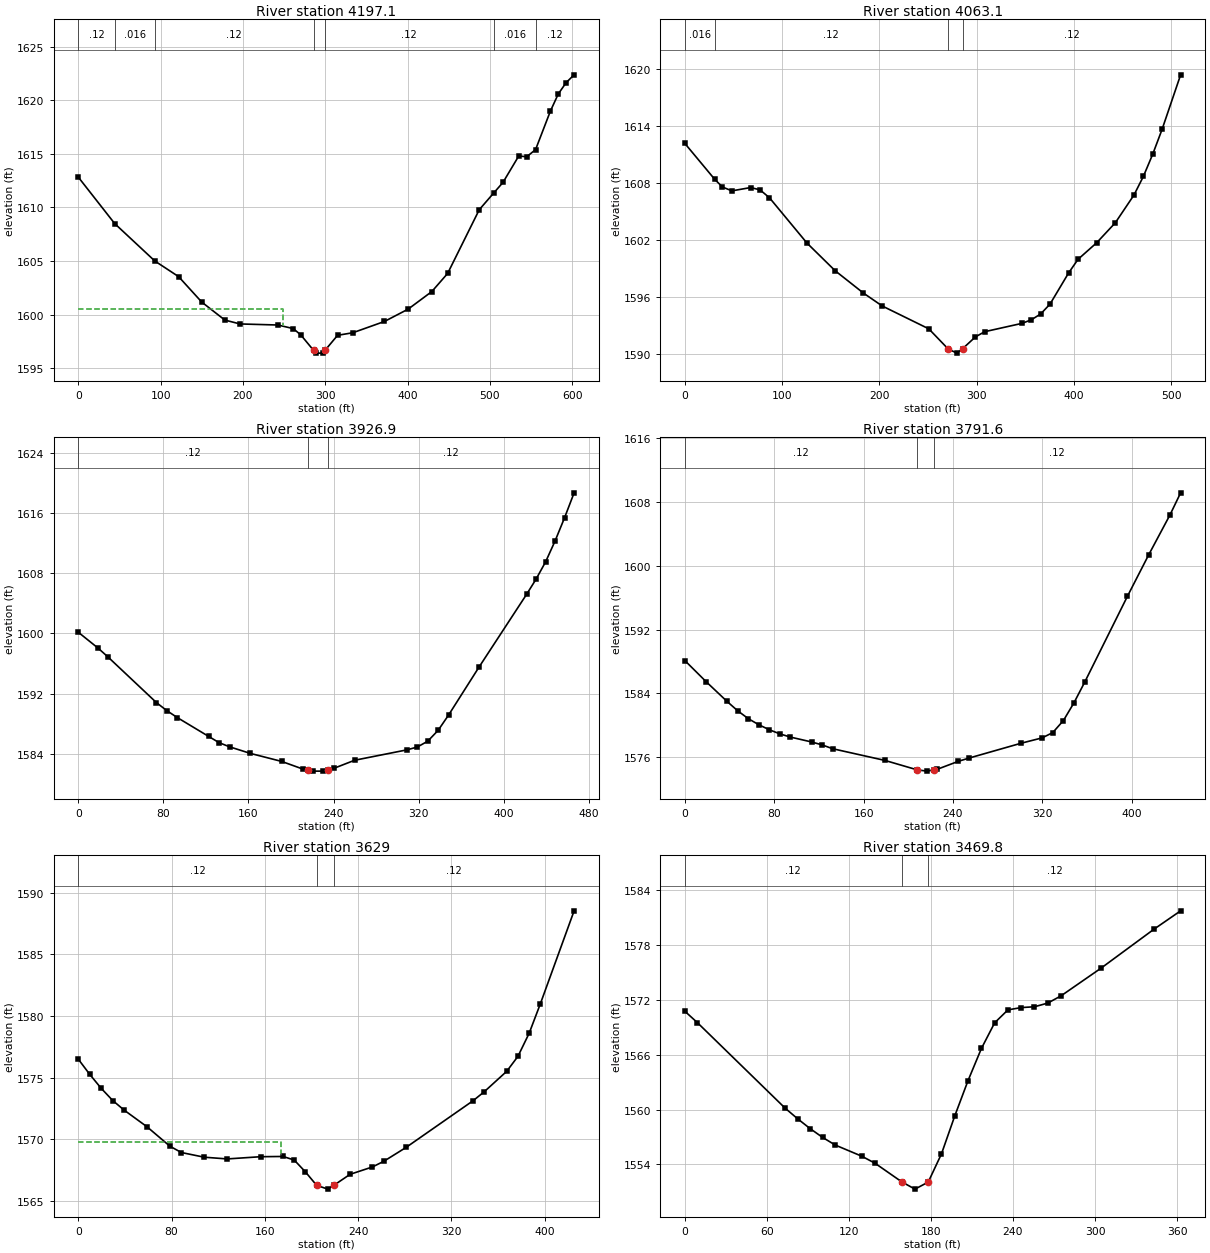
Type RM Length L Ch R = 1 ,4197.1  ,129.1,134,130
XS GIS Cut Line= 5
     1814631.499      227261.204     1814626.291      227439.155
     1814699.208      227509.467     1814703.548      227553.738
     1814950.076      227683.079
#Sta/Elev= 30
       0 1612.82   44.161608.496   92.821605.013   121.8 1603.55   149.9 1601.18
     178  1599.5   196.4 1599.14   242.5 1599.04   260.9 1598.71   270.1 1598.13
  285.691596.682   288.2 1596.42   297.1 1596.42  299.711596.686   314.9 1598.08
   333.4 1598.32   371.8 1599.37   400.6 1600.52   429.4 1602.16   448.6 1603.85
     487 1609.79  504.431611.335   515.8 1612.33     535  1614.8   544.6 1614.72
   555.41615.391   573.4 1618.98     583 1620.58   592.6 1621.64   602.2 1622.36
#Mann= 7 ,-1 , 0
       0     .12       0   44.16    .016       0   92.82     .12       0
  285.69    .045       0  299.71     .12       0  504.43    .016       0
   555.4     .12       0
#XS Ineff= 2 , 0
           248.5 1600.52
Permanent Ineff=
       F       F
Bank Sta=285.69,299.71
XS Rating Curve= 0 ,0
Exp/Cntr=0.3,0.1

Type RM Length L Ch R = 1 ,4063.1  ,135.1,136.1,137.1
XS GIS Cut Line= 3
     1814562.029      227277.165     1814549.536      227479.556
     1814633.223      227774.663
#Sta/Elev= 30
       0  1612.2   30.611608.426    38.6 1607.61    48.3  1607.2    67.6 1607.55
    77.2 1607.31    86.9 1606.48   125.5  1601.7   154.5 1598.78   183.5 1596.43
   202.8 1595.07   250.7 1592.66   270.5 1590.55   279.5  1590.1   285.5 1590.57
   298.6 1591.81   308.2 1592.36   346.6 1593.24   356.2 1593.62   365.7 1594.23
   375.3 1595.27   394.5 1598.57   404.1 1599.99   423.2 1601.73   442.4 1603.84
   461.6 1606.77   471.2 1608.72   480.8 1611.06   490.4 1613.67   509.5 1619.43
#Mann= 4 ,-1 , 0
       0    .016       0   30.61     .12       0   270.5    .045       0
   285.5     .12       0
Bank Sta=270.5,285.5
XS Rating Curve= 0 ,0
Exp/Cntr=0.3,0.1

Type RM Length L Ch R = 1 ,3926.9  ,138.4,135.3,132
XS GIS Cut Line= 4
     1814406.423      227365.291     1814403.702      227438.757
     1814471.411      227725.216     1814520.552       227810.53
#Sta/Elev= 30
       0 1600.16    18.4 1598.07    27.6 1596.91    73.5 1590.79    83.3 1589.72
    93.1  1588.8   122.6 1586.29   132.4 1585.46   142.2 1584.91   161.8 1584.03
   191.3 1582.96   210.9 1581.96  216.091581.806   220.7 1581.67   230.5 1581.67
  234.791581.829   240.3 1582.04   259.9 1583.12     309  1584.5   318.8 1584.88
   328.6 1585.65   338.4  1587.1   348.2 1589.13   376.8 1595.51   421.6 1605.21
   430.5 1607.23   439.5 1609.54   448.4 1612.32   457.4 1615.44   466.3 1618.73
#Mann= 3 ,-1 , 0
       0     .12       0  216.09    .045       0  234.79     .12       0
Bank Sta=216.09,234.79
XS Rating Curve= 0 ,0
Exp/Cntr=0.3,0.1

Type RM Length L Ch R = 1 ,3791.6  ,156.6,162.6,168.5
XS GIS Cut Line= 4
     1814325.076      227433.079     1814281.673      227558.079
     1814350.249      227732.558     1814428.374      227828.912
#Sta/Elev= 29
       0 1588.11    18.9 1585.48    37.8 1582.98    47.3 1581.81    56.7 1580.83
    66.2 1580.06    75.6 1579.43    85.1 1578.91    94.5 1578.51   113.4  1577.9
   122.9 1577.53   132.3 1577.05   179.2 1575.58     208  1574.4   216.7 1574.24
     223  1574.4   226.1 1574.48   244.8 1575.47   254.2 1575.87     301 1577.74
   319.8 1578.41   329.3 1579.07   338.9 1580.59   348.4 1582.83     358 1585.42
   396.1 1596.15   415.2 1601.37   434.3 1606.39   443.8 1609.15
#Mann= 3 ,-1 , 0
       0     .12       0     208    .045       0     223     .12       0
Bank Sta=208,223
XS Rating Curve= 0 ,0
Exp/Cntr=0.3,0.1

Type RM Length L Ch R = 1 ,3629    ,164,159.2,154.4
XS GIS Cut Line= 4
     1814150.451      227475.188     1814153.702       227602.82
      1814181.48       227821.57     1814229.736      227881.755
#Sta/Elev= 28
       0  1576.5     9.8 1575.27    19.6 1574.14    29.5 1573.15    39.3 1572.37
    58.9 1571.02    78.6 1569.44    88.4 1568.93     108 1568.55   127.7 1568.41
   156.4 1568.59   175.6 1568.61   185.2 1568.32   194.8 1567.36   204.4 1566.27
     214 1565.96  219.571566.294   233.1 1567.16   252.3 1567.76   261.9 1568.21
   281.1 1569.34   338.6 1573.13   348.2 1573.86   367.5 1575.52   377.1 1576.73
   386.8 1578.62   396.4 1581.01   425.3 1588.54
#Mann= 3 ,-1 , 0
       0     .12       0   204.4    .045       0  219.57     .12       0
#XS Ineff= 2 , 0
          173.89 1569.81
Permanent Ineff=
       F       F
Bank Sta=204.4,219.57
XS Rating Curve= 0 ,0
Exp/Cntr=0.3,0.1

Type RM Length L Ch R = 1 ,3469.8  ,230.7,229.1,227.5
XS GIS Cut Line= 3
     1814009.708      227570.372      1813993.98      227679.209
     1814077.368      227917.698
#Sta/Elev= 25
       0 1570.75     9.2  1569.5    73.3 1560.16    82.5 1558.99    91.6 1557.92
   100.8 1556.95     110 1556.12   129.4  1554.9   139.1 1554.13   158.6  1552.1
   168.3  1551.3     178 1552.07   187.7 1555.16   197.4  1559.3   207.1 1563.16
   216.9 1566.68   226.6 1569.49   236.3  1570.9     246 1571.15   255.7 1571.24
   265.4 1571.64   275.2 1572.44   304.3 1575.45   343.2 1579.73   362.6 1581.73
#Mann= 3 ,-1 , 0
       0     .12       0   158.6    .045       0     178     .12       0
Bank Sta=158.6,178
XS Rating Curve= 0 ,0
Exp/Cntr=0.3,0.1

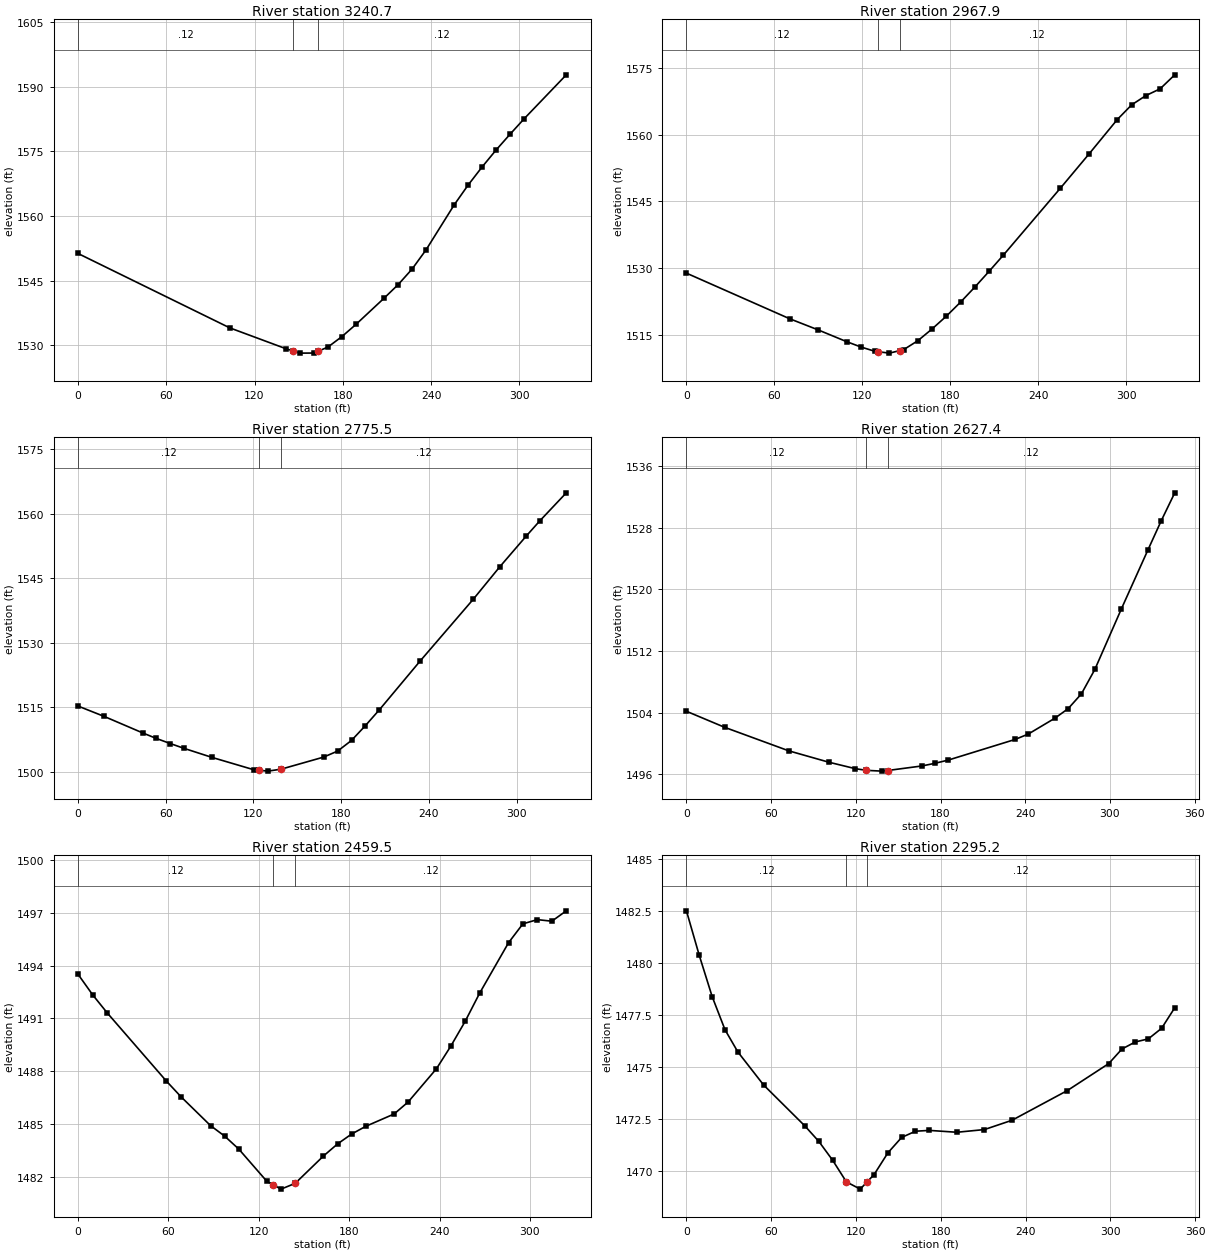
Type RM Length L Ch R = 1 ,3240.7  ,269.5,272.9,274.5
XS GIS Cut Line= 3
     1813810.672      227677.198     1813782.175      227776.431
     1813872.845      227986.298
#Sta/Elev= 21
       0 1551.33   103.2 1534.06   141.4 1529.22  146.181528.707   150.9  1528.2
   160.4 1528.22  163.26 1528.64   169.9 1529.61   179.4 1532.04     189 1534.88
     208 1540.93   217.6 1544.09   227.1 1547.71   236.6 1552.17   255.7  1562.6
   265.2 1567.21   274.7 1571.41   284.2 1575.34   293.8 1579.04   303.3  1582.6
   331.9 1592.78
#Mann= 3 ,-1 , 0
       0     .12       0  146.18    .045       0  163.26     .12       0
Bank Sta=146.18,163.26
XS Rating Curve= 0 ,0
Exp/Cntr=0.3,0.1

Type RM Length L Ch R = 1 ,2967.9  ,192.8,192.4,191.9
XS GIS Cut Line= 4
     1813582.571      227760.766     1813563.425      227828.514
     1813653.702      228075.042     1813653.939      228075.229
#Sta/Elev= 24
       0 1528.84    70.4 1518.56    89.8 1516.05   109.3 1513.39     119 1512.19
   128.7  1511.2   130.5 1511.13   138.5  1510.8   145.5 1511.36   148.2 1511.58
   157.9  1513.6   167.6 1516.25   177.4 1519.15   187.1 1522.32   196.8  1525.7
   206.5 1529.24   216.3 1532.92   255.2 1548.02   274.6 1555.68     294 1563.49
   303.8  1566.8   313.5 1568.89   323.2 1570.41   333.2 1573.57
#Mann= 3 ,-1 , 0
       0     .12       0   130.5    .045       0   145.5     .12       0
Bank Sta=130.5,145.5
XS Rating Curve= 0 ,0
Exp/Cntr=0.3,0.1

Type RM Length L Ch R = 1 ,2775.5  ,148.7,148.1,147.5
XS GIS Cut Line= 4
      1813388.91      227831.717     1813377.661       227884.07
     1813436.689      228035.112     1813519.955      228119.156
#Sta/Elev= 22
       0 1515.28    17.8 1512.88    44.6 1508.98    53.6 1507.74    63.1 1506.56
    72.6 1505.43    91.7 1503.33   120.3 1500.46   123.9 1500.34   129.9 1500.14
   138.9 1500.59     168  1503.4   177.6  1504.8   187.1 1507.28   196.6 1510.72
   206.2 1514.42   233.9 1525.69   270.3 1540.08   288.5 1547.65   306.7 1554.84
   315.8 1558.31     334 1564.86
#Mann= 3 ,-1 , 0
       0     .12       0   123.9    .045       0   138.9     .12       0
Bank Sta=123.9,138.9
XS Rating Curve= 0 ,0
Exp/Cntr=0.3,0.1

Type RM Length L Ch R = 1 ,2627.4  ,168.8,167.9,166.9
XS GIS Cut Line= 4
     1813253.093       227881.57      1813243.98      227953.514
     1813309.952      228109.764      1813408.15      228143.224
#Sta/Elev= 21
       0 1504.19    27.2  1502.1    72.5 1499.06   100.8 1497.59   119.6 1496.75
   127.5 1496.53   138.5 1496.43   142.5 1496.51   166.8  1497.1   176.2 1497.45
   185.6 1497.87   232.7 1500.53   242.1 1501.23     261 1503.29   270.4 1504.53
   279.8 1506.45   289.3 1509.61   308.1 1517.46     327 1525.14   336.4 1528.91
   345.9  1532.5
#Mann= 3 ,-1 , 0
       0     .12       0   127.5    .045       0   142.5     .12       0
Bank Sta=127.5,142.5
XS Rating Curve= 0 ,0
Exp/Cntr=0.3,0.1

Type RM Length L Ch R = 1 ,2459.5  ,162.6,164.3,166
XS GIS Cut Line= 4
      1813092.38      227956.001     1813098.147      228043.792
     1813162.383      228179.209     1813243.729      228207.741
#Sta/Elev= 27
       0 1493.52     9.8 1492.34    19.6  1491.3    58.6 1487.45    68.4 1486.55
      88 1484.91    97.4 1484.31   106.7 1483.58   125.4 1481.74  129.691481.542
   134.8  1481.3   144.2 1481.63   162.9 1483.18   172.3 1483.87   181.6 1484.43
     191 1484.87   209.8 1485.57   219.1 1486.25   237.9 1488.14   247.4 1489.42
     257 1490.84   266.6 1492.44   285.8 1495.31   295.3 1496.38   304.9 1496.62
   314.5 1496.53   324.1 1497.12
#Mann= 3 ,-1 , 0
       0     .12       0  129.69    .045       0   144.2     .12       0
Bank Sta=129.69,144.2
XS Rating Curve= 0 ,0
Exp/Cntr=0.3,0.1

Type RM Length L Ch R = 1 ,2295.2  ,171.8,170.2,168.6
XS GIS Cut Line= 4
     1812941.541      228021.533     1812939.575      228076.105
     1813026.966      228304.209     1813072.105      228316.319
#Sta/Elev= 27
       0 1482.52     9.1 1480.37    18.2 1478.39    27.3 1476.79    36.4 1475.72
    54.6 1474.13    83.9 1472.15    93.7 1471.41   103.5  1470.5   113.2 1469.46
     123 1469.11  127.791469.455   132.8 1469.81   142.6 1470.86   152.3  1471.6
   162.1  1471.9   171.9 1471.94   191.4 1471.85   210.9 1471.98   230.5 1472.43
   269.6 1473.86   298.9 1475.16   308.2 1475.86   317.6  1476.2   326.9 1476.35
   336.3 1476.86   345.6 1477.85
#Mann= 3 ,-1 , 0
       0     .12       0   113.2    .045       0  127.79     .12       0
Bank Sta=113.2,127.79
XS Rating Curve= 0 ,0
Exp/Cntr=0.3,0.1