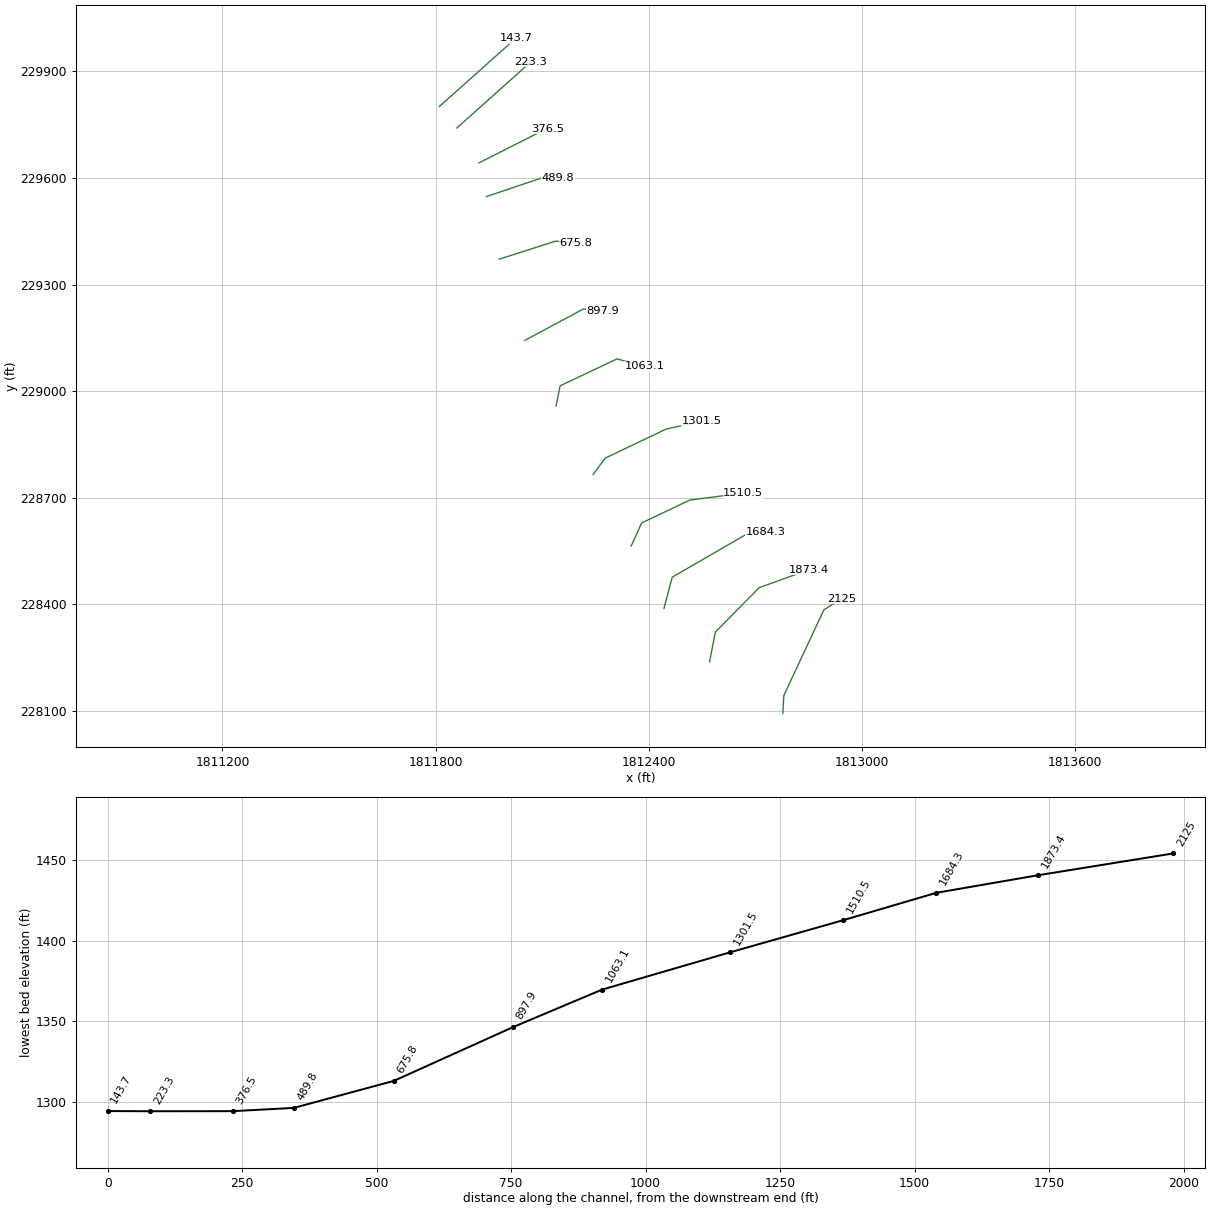
HEC-RAS study LLAURELRN.prj: LLAURELRN

--- LLAURELRN.g01 (geometry) --- (continued)

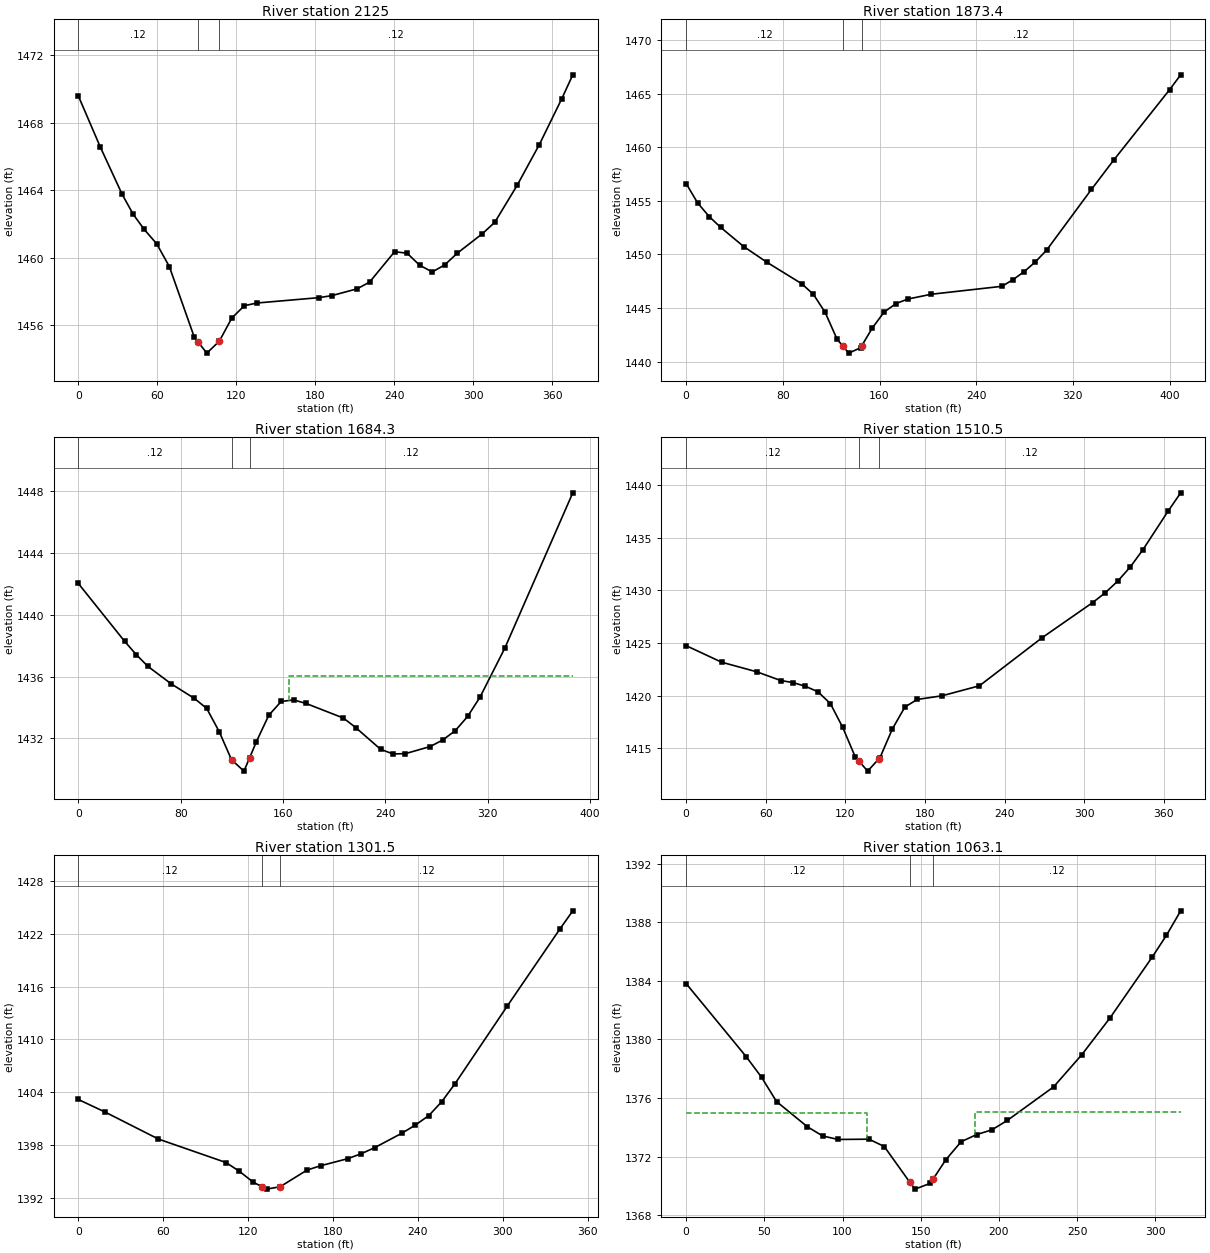
Type RM Length L Ch R = 1 ,2125    ,259.3,251.6,243.8
XS GIS Cut Line= 4
     1812777.757      228092.689     1812780.439       228142.75
     1812893.286       228384.07     1812943.462      228415.703
#Sta/Elev= 30
       0  1469.6    16.7 1466.57    33.4 1463.75    41.8 1462.57    50.1 1461.68
    59.6 1460.83    69.2 1459.48    88.2 1455.29   91.011455.012    97.7 1454.35
   107.2 1455.06   116.7 1456.43   126.2 1457.16   135.8 1457.32   183.3 1457.64
   192.8 1457.76   211.9 1458.16   221.4 1458.56   240.4 1460.36   249.9 1460.27
   259.4 1459.56     269 1459.16   278.5 1459.58     288 1460.27     307 1461.42
   316.5  1462.1   333.5 1464.29   350.4 1466.71   367.4 1469.42   375.8 1470.84
#Mann= 3 ,-1 , 0
       0     .12       0   91.01    .045       0   107.2     .12       0
Bank Sta=91.01,107.2
XS Rating Curve= 0 ,0
Exp/Cntr=0.3,0.1

Type RM Length L Ch R = 1 ,1873.4  ,195.1,189,183
XS GIS Cut Line= 4
     1812571.399      228237.363      1812587.73       228321.57
     1812710.994       228446.57     1812850.102       228496.69
#Sta/Elev= 28
       0 1456.61     9.5  1454.8    19.1 1453.53    28.6 1452.52    47.6 1450.74
    66.7 1449.28    95.5 1447.28   105.3 1446.28     115  1444.6   124.8 1442.11
  129.791441.436   134.5  1440.8   144.3  1441.3  145.231441.476     154 1443.14
   163.8 1444.63   173.6 1445.42   183.3 1445.84   202.8 1446.29   261.3 1447.03
   270.6 1447.66   279.8 1448.41     289 1449.31   298.3 1450.41   335.3 1456.06
   353.7 1458.79     400 1465.36   409.2 1466.75
#Mann= 3 ,-1 , 0
       0     .12       0  129.79    .045       0  145.23     .12       0
Bank Sta=129.79,145.23
XS Rating Curve= 0 ,0
Exp/Cntr=0.3,0.1

Type RM Length L Ch R = 1 ,1684.3  ,175.6,173.8,172
XS GIS Cut Line= 4
     1812443.121      228388.374     1812466.202      228476.084
     1812676.272      228597.612     1812729.016      228604.205
#Sta/Elev= 28
       0 1442.02    36.3 1438.27    45.4 1437.41    54.4 1436.66    72.6 1435.53
    90.7 1434.59   100.4 1433.94   110.1 1432.45   119.8 1430.62   129.5 1429.89
  133.931430.754   139.2 1431.79   148.9  1433.5   158.6 1434.39   168.4 1434.49
   178.1 1434.26   207.2 1433.32   216.9  1432.7   236.3  1431.3     246    1431
   255.7 1431.02   275.1 1431.48   284.8  1431.9   294.6  1432.5   304.3 1433.42
     314 1434.67   333.4 1437.84   386.5 1447.87
#Mann= 3 ,-1 , 0
       0     .12       0   119.8    .045       0  133.93     .12       0
#XS Ineff= 2 , 0
                          164.71         1436.06
Permanent Ineff=
       F       F
Bank Sta=119.8,133.93
XS Rating Curve= 0 ,0
Exp/Cntr=0.3,0.1

Type RM Length L Ch R = 1 ,1510.5  ,209,209,209.1
XS GIS Cut Line= 4
     1812350.838      228563.982     1812380.245      228628.816
     1812515.584      228693.215     1812666.095      228712.655
#Sta/Elev= 27
       0 1424.74    26.7 1423.17    53.4 1422.25    71.2 1421.43    80.6 1421.23
    89.9 1420.88    99.3 1420.36   108.7 1419.24     118 1416.98   127.4 1414.19
   130.2 1413.78   136.8 1412.82   145.2 1413.98   146.1  1414.1   155.5 1416.84
   164.9 1418.91   174.2 1419.63     193 1419.98   221.1 1420.93   268.5 1425.51
   306.4 1428.83   315.9 1429.76   325.4 1430.88   334.9 1432.23   344.4 1433.87
   363.4 1437.54   372.8 1439.26
#Mann= 3 ,-1 , 0
       0     .12       0   130.2    .045       0   145.2     .12       0
Bank Sta=130.2,145.2
XS Rating Curve= 0 ,0
Exp/Cntr=0.3,0.1

Type RM Length L Ch R = 1 ,1301.5  ,238.5,238.5,238.3
XS GIS Cut Line= 4
     1812243.798      228765.177     1812277.035      228811.009
     1812449.469      228893.337     1812548.846      228914.742
#Sta/Elev= 22
       0 1403.17    18.9 1401.74    56.6 1398.67   104.4    1396   113.9    1395
   123.5 1393.78  129.961393.238     133 1392.98   142.6 1393.25   161.7 1395.15
   171.3 1395.64   190.4 1396.44   199.9    1397   209.5  1397.7   228.6 1399.33
   238.1 1400.25   247.7 1401.34   256.9 1402.93   266.2 1404.96   303.1 1413.78
   340.1 1422.49   349.4  1424.6
#Mann= 3 ,-1 , 0
       0     .12       0  129.96    .045       0   142.6     .12       0
Bank Sta=129.96,142.6
XS Rating Curve= 0 ,0
Exp/Cntr=0.3,0.1

Type RM Length L Ch R = 1 ,1063.1  ,164,165.2,166.3
XS GIS Cut Line= 4
     1812139.312      228958.252     1812150.746      229014.925
     1812310.851        229090.7     1812389.312      229069.363
#Sta/Elev= 24
       0 1383.81    38.5 1378.81    48.2 1377.42    57.8 1375.76    77.5 1374.04
    87.3 1373.41    97.2 1373.17   116.9 1373.19   126.7 1372.69   142.9 1370.27
   146.4 1369.78   156.2 1370.18   157.9 1370.46   166.1 1371.79   175.9 1373.02
   185.7  1373.5   195.6 1373.83   205.4 1374.47     235 1376.76     253 1378.95
   271.1 1381.47   298.2 1385.64   307.2 1387.11   316.3 1388.78
#Mann= 3 ,-1 , 0
       0     .12       0   142.9    .045       0   157.9     .12       0
#XS Ineff= 2 , 0
          115.58 1375.01  184.93         1375.05
Permanent Ineff=
       F       F
Bank Sta=142.9,157.9
XS Rating Curve= 0 ,0
Exp/Cntr=0.3,0.1

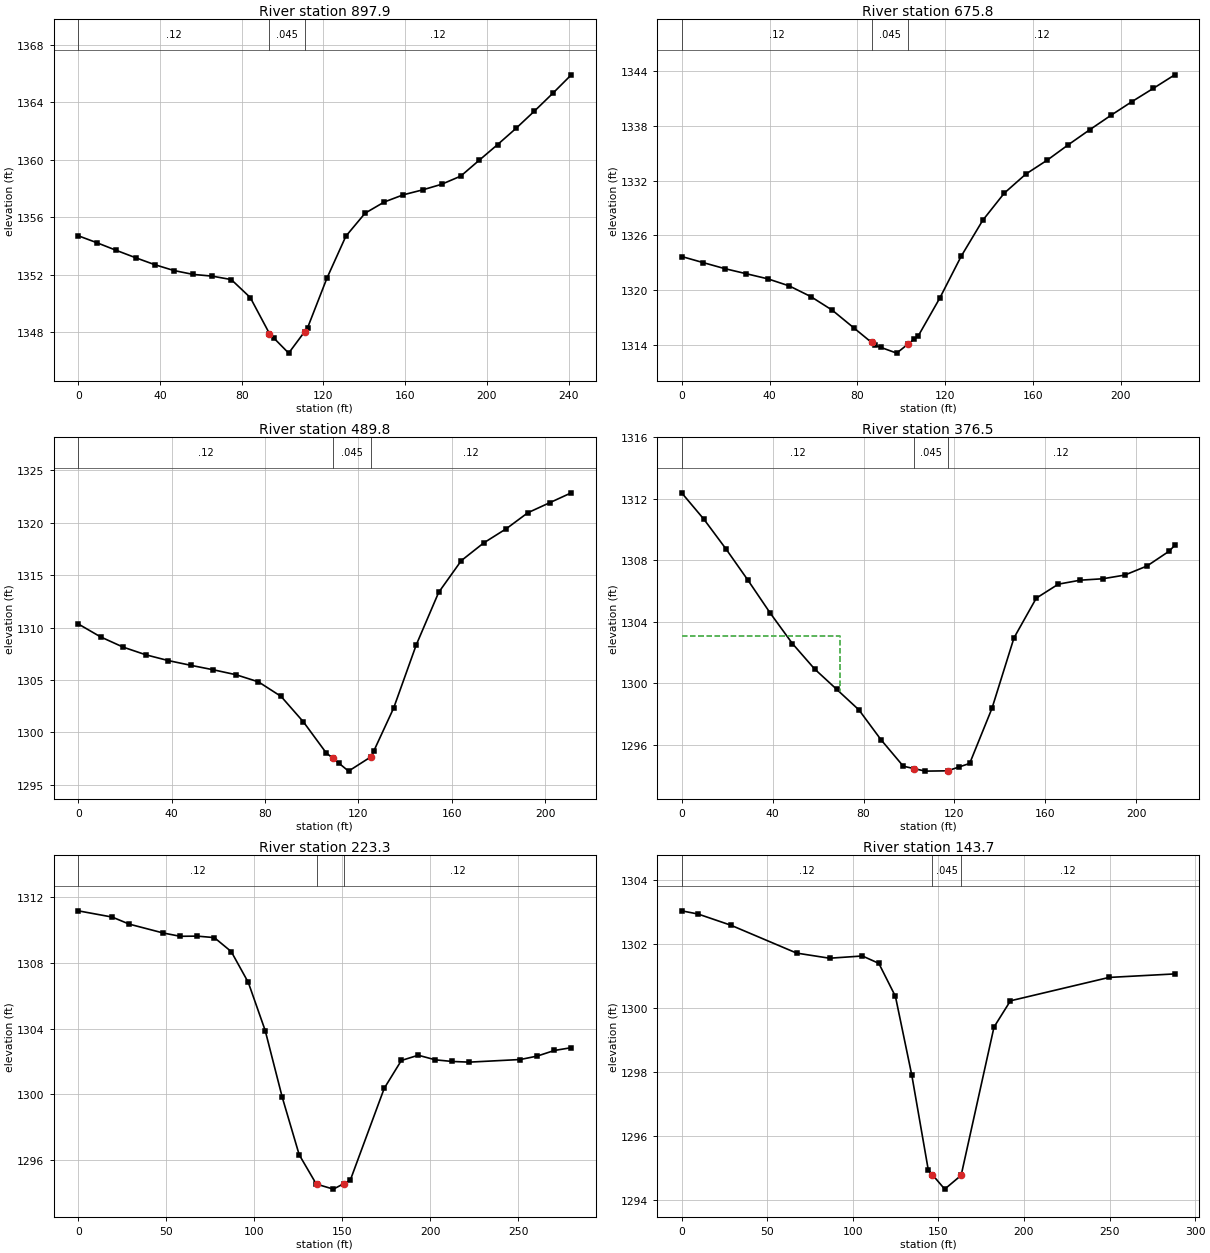
Type RM Length L Ch R = 1 ,897.9   ,226.3,222.1,218
XS GIS Cut Line= 3
     1812051.272       229142.75     1812216.202      229231.292
     1812270.097       229226.22
#Sta/Elev= 29
       0 1354.71     9.4 1354.21    18.7 1353.69    28.1 1353.18    37.4  1352.7
    46.8 1352.29    56.2 1352.02    65.5  1351.9    74.9 1351.66    84.2 1350.41
    93.6  1347.9    95.8 1347.58     103 1346.54   110.8 1348.03   112.3 1348.32
   121.7 1351.75     131 1354.68   140.4 1356.28   149.8 1357.06   159.1 1357.56
   168.5  1357.9   177.8 1358.29   187.2 1358.86   196.2 1359.96   205.2 1361.05
   214.3 1362.19   223.3 1363.39   232.3 1364.63   241.3 1365.91
#Mann= 3 ,-1 , 0
       0     .12       0    93.6    .045       0   110.8     .12       0
Bank Sta=93.6,110.8
XS Rating Curve= 0 ,0
Exp/Cntr=0.3,0.1

Type RM Length L Ch R = 1 ,675.8   ,185.5,185.9,186.3
XS GIS Cut Line= 3
     1811979.477      229371.676     1812138.077      229422.264
     1812195.844      229417.158
#Sta/Elev= 28
       0 1323.68     9.8 1323.01    19.6 1322.35    29.4 1321.79    39.2 1321.23
      49 1320.45    58.8 1319.28    68.6 1317.78    78.3 1315.86   86.491314.239
    88.1 1313.92    90.8 1313.69    97.9 1313.07   103.1 1314.07   105.8 1314.59
   107.7 1314.95   117.5  1319.1   127.3 1323.72   137.1 1327.66   146.9 1330.64
   156.7 1332.73   166.5 1334.27   176.1 1335.96   185.8  1337.6   195.5 1339.19
   205.1  1340.7   214.8 1342.15   224.5 1343.63
#Mann= 3 ,-1 , 0
       0     .12       0   86.49    .045       0   103.1     .12       0
Bank Sta=86.49,103.1
XS Rating Curve= 0 ,0
Exp/Cntr=0.3,0.1

Type RM Length L Ch R = 1 ,489.8   ,110.1,113.3,116.6
XS GIS Cut Line= 3
     1811943.423      229547.899     1812117.244      229606.292
     1812144.083      229599.114
#Sta/Elev= 26
       0 1310.35     9.6 1309.11    19.3 1308.13      29  1307.4    38.6 1306.85
    48.2  1306.4    57.9 1305.97    67.6  1305.5    77.2 1304.82    86.9 1303.43
    96.5 1300.99   106.2 1298.05  109.151297.514   111.7 1297.05   115.8  1296.3
   125.5 1297.68   126.7 1298.26   135.1 1302.31   144.8 1308.35   154.4 1313.36
   164.1 1316.39   173.7 1318.08   183.4 1319.44   192.6 1320.96   201.9 1321.91
   211.2 1322.86
#Mann= 3 ,-1 , 0
       0     .12       0  109.15    .045       0   125.5     .12       0
Bank Sta=109.15,125.5
XS Rating Curve= 0 ,0
Exp/Cntr=0.3,0.1

Type RM Length L Ch R = 1 ,376.5   ,147.1,153.2,159.4
XS GIS Cut Line= 3
     1811922.433      229642.775     1812113.854      229739.408
     1812116.202      229738.522
#Sta/Elev= 26
       0 1312.38     9.8 1310.66    19.5 1308.73    29.2 1306.69      39 1304.55
    48.7 1302.58    58.5 1300.92    68.2  1299.6      78 1298.26    87.7 1296.32
    97.5  1294.6   102.41294.438   107.2 1294.28     117  1294.3   122.2 1294.56
   126.7 1294.78   136.5 1298.36   146.2 1302.95     156 1305.53   165.7 1306.44
   175.4  1306.7   185.2 1306.79   194.9 1307.03   204.7 1307.62   214.4 1308.58
   216.9 1308.96
#Mann= 3 ,-1 , 0
       0     .12       0   102.4    .045       0     117     .12       0
#XS Ineff= 2 , 0
           69.66 1303.09
Permanent Ineff=
       F       F
Bank Sta=102.4,117
XS Rating Curve= 0 ,0
Exp/Cntr=0.3,0.1

Type RM Length L Ch R = 1 ,223.3   ,79.8,79.5,79.3
XS GIS Cut Line= 2
     1811859.992      229740.901     1812068.895      229927.422
#Sta/Elev= 27
       0 1311.17    19.3 1310.79      29 1310.36    48.3 1309.82    57.9 1309.62
    67.6 1309.63    77.3 1309.54    86.9 1308.69    96.6 1306.81   106.2 1303.88
   115.9 1299.81   125.5 1296.32   135.2 1294.54   135.8 1294.52   144.9 1294.23
   150.8 1294.56   154.5 1294.77   173.8 1300.37   183.5 1302.06   193.1 1302.38
   202.8  1302.1   212.5    1302   222.1 1301.96   251.1 1302.12   260.7 1302.33
   270.4 1302.67     280 1302.84
#Mann= 3 ,-1 , 0
       0     .12       0   135.8    .045       0   150.8     .12       0
Bank Sta=135.8,150.8
XS Rating Curve= 0 ,0
Exp/Cntr=0.3,0.1

Type RM Length L Ch R = 1 ,143.7   ,143,143.7,143.3
XS GIS Cut Line= 2
     1811810.815      229801.347     1812025.743      229993.246
#Sta/Elev= 17
       0 1303.03     9.6 1302.93    28.8 1302.58    67.2 1301.71    86.4 1301.55
   105.6 1301.62   115.2 1301.39   124.9 1300.36   134.5 1297.89   144.1 1294.94
   146.5 1294.79   153.7 1294.34   163.3 1294.77   182.5  1299.4   192.1 1300.22
   249.7 1300.95   288.1 1301.06
#Mann= 3 ,-1 , 0
       0     .12       0   146.5    .045       0   163.3     .12       0
Bank Sta=146.5,163.3
XS Rating Curve= 0 ,0
Exp/Cntr=0.3,0.1

Chan Stop Cuts=-1
Use User Specified Reach Order=0
Composite Channel Slope=5